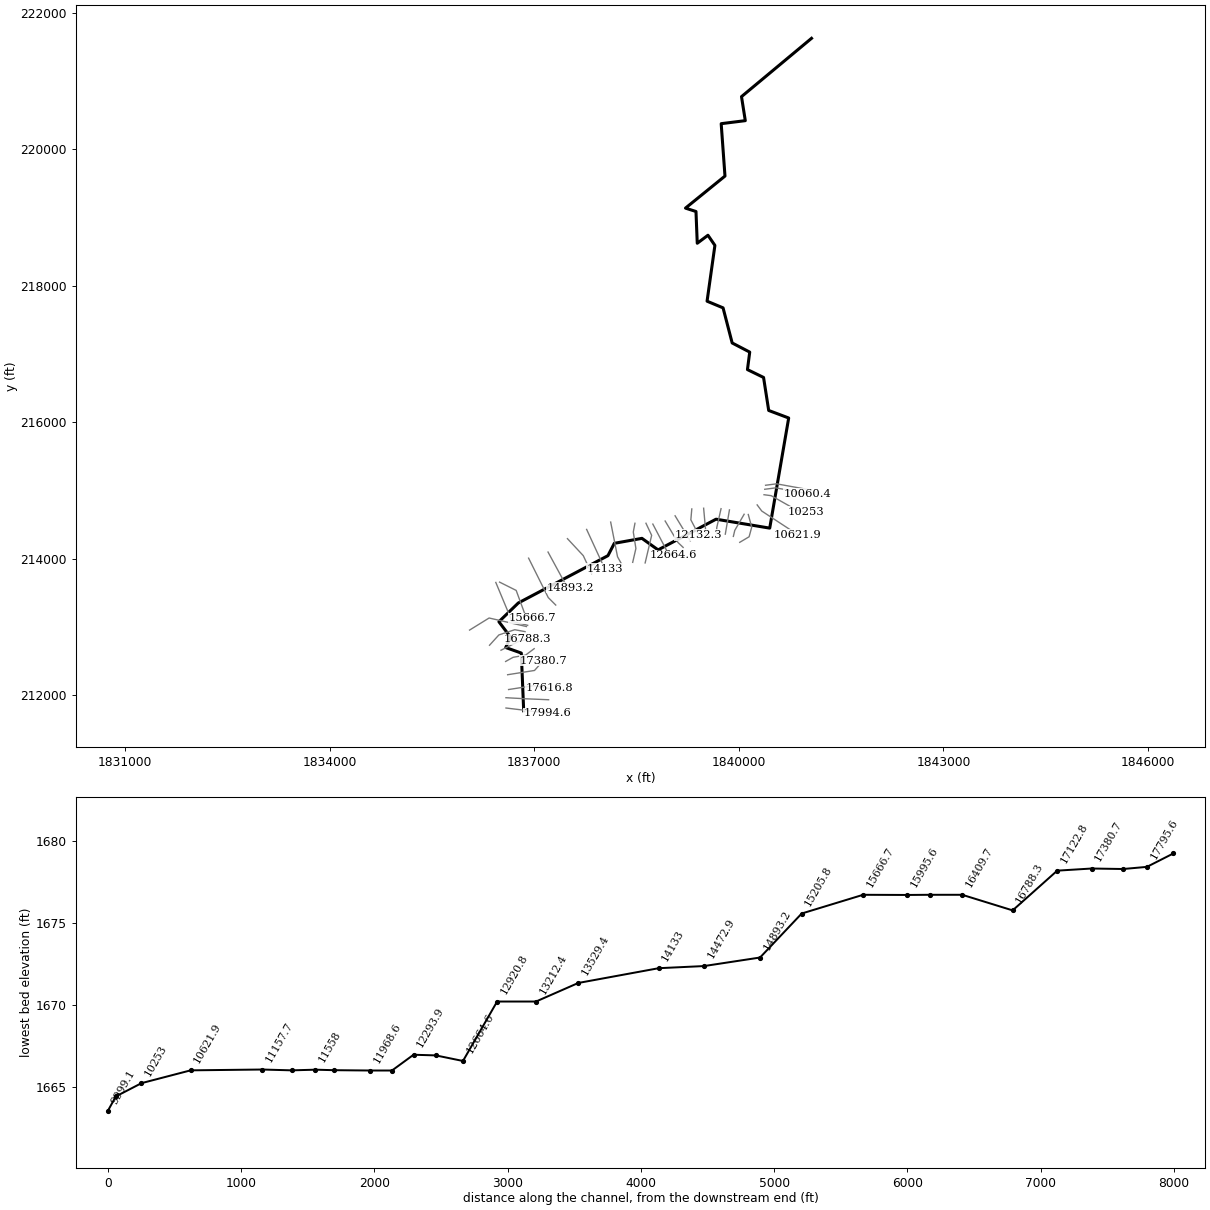
--- BILLSCK.prj (project) ---

Proj Title=BILLSCK
Current Plan=p01
Default Exp/Contr=0,0
English Units
Geom File=g01
Flow File=f01
Plan File=p01
BEGIN DESCRIPTION:
END DESCRIPTION:
DSS Export Rating Curves= 0
DSS Export Rating Curve Sorted= 0
DSS Export Volume Flow Curves= 0
DXF OffsetX= 0
DXF OffsetY= 0
DXF ScaleX= 0
DXF ScaleY= 0

--- BILLSCK.p01 (plan) ---

Plan Title=Floodplain
Program Version=4.00
Geom File=g01
Flow File=f01
K Sum by GR=0
Std Step Tol=0.01
Critical Tol=0.01
Num of Std Step Trials=20
Max Error Tol=0.3
Flow Tol Ratio=0.001
Split Flow NTrial=30
Split Flow Tol=0.02
Split Flow Ratio=0.02
Log Output Level=0
Friction Slope Method=1
Unsteady Friction Slope Method=2
Unsteady Bridges Friction Slope Method=1
Global Log Level=0
CheckData=False
Run HTab=0
Run UNet=0
Run PostProcess=0
UNET Theta=0
UNET Theta Warmup=0
UNET ZTol=0
UNET ZSATol=0
UNET MxIter=0
UNET MaxInSteps=0
UNET DtIC=0
UNET DtMin=0
UNET MaxCRTS=0
UNET WFStab=0
UNET SFStab=0
UNET WFX=0
UNET SFX=0
UNET DSS MLevel=0
UNET DZMax Abort=0
UNET Convert EG Bridges=0
UNET Use Existing IB Tables=0
UNET Froude Limit=0
UNET Froude Power=0
Write IC File=0
Echo Input=False
Echo Output=False
Write Detailed=0

--- BILLSCK.f01 (steady flow) ---

Flow Title=NFF Regression Equation
Program Version=5.03
Number of Profiles= 1
Profile Names=P100yr
River Rch & RM=BILLSCK,Main            ,17994.6
633.4151
River Rch & RM=BILLSCK,Main            ,16788.3
645.0869
River Rch & RM=BILLSCK,Main            ,15995.6
715.4144
River Rch & RM=BILLSCK,Main            ,15205.8
767.6421
River Rch & RM=BILLSCK,Main            ,12664.6
812.3141
River Rch & RM=BILLSCK,Main            ,10060.4
  892.44
River Rch & RM=BILLSCK,Main            ,7637
946.1629
River Rch & RM=BILLSCK,Main            ,4168.6
1015.556
River Rch & RM=BILLSCK,Main            ,2705.8
1124.388
River Rch & RM=BILLSCK,Main            ,877.2
1139.166
River Rch & RM=BILLSCK,Main            ,469.7
1142.357
Boundary for River Rch & Prof#=BILLSCK,Main            , 1
Up Type= 0
Dn Type= 3
Dn Slope=0.027635
DSS Import GetInterval= 0
DSS Import GetPeak= 0
DSS Import FillOption= 0

--- BILLSCK.g01 (geometry) ---

Geom Title=USGS 10m DEM
Program Version=4.10

River Reach=BILLSCK         ,Main
Reach XY= 30
     1836846.432      211768.873     1836811.555      212615.193
     1836583.007      212696.356     1836654.554      212847.888
     1836482.958      213074.672     1836767.151      213349.236
      1838081.56      214043.281     1838174.948      214224.269
      1838579.92      214297.071     1838816.854       214127.87
     1839666.273      214577.943     1840453.311      214446.958
     1840731.455       216061.55     1840438.317      216171.964
      1840362.99      216655.834      1840126.79      216770.991
     1840160.128      217027.437     1839902.927      217161.383
     1839769.301       217676.01     1839534.753      217773.784
     1839649.764      218591.611     1839547.787      218740.524
     1839390.942      218623.078     1839372.272      219088.683
     1839218.298      219138.283     1839797.317      219608.095
     1839741.779       220376.43     1840095.189      220420.627
     1840039.633       220772.71     1841065.951      221627.399

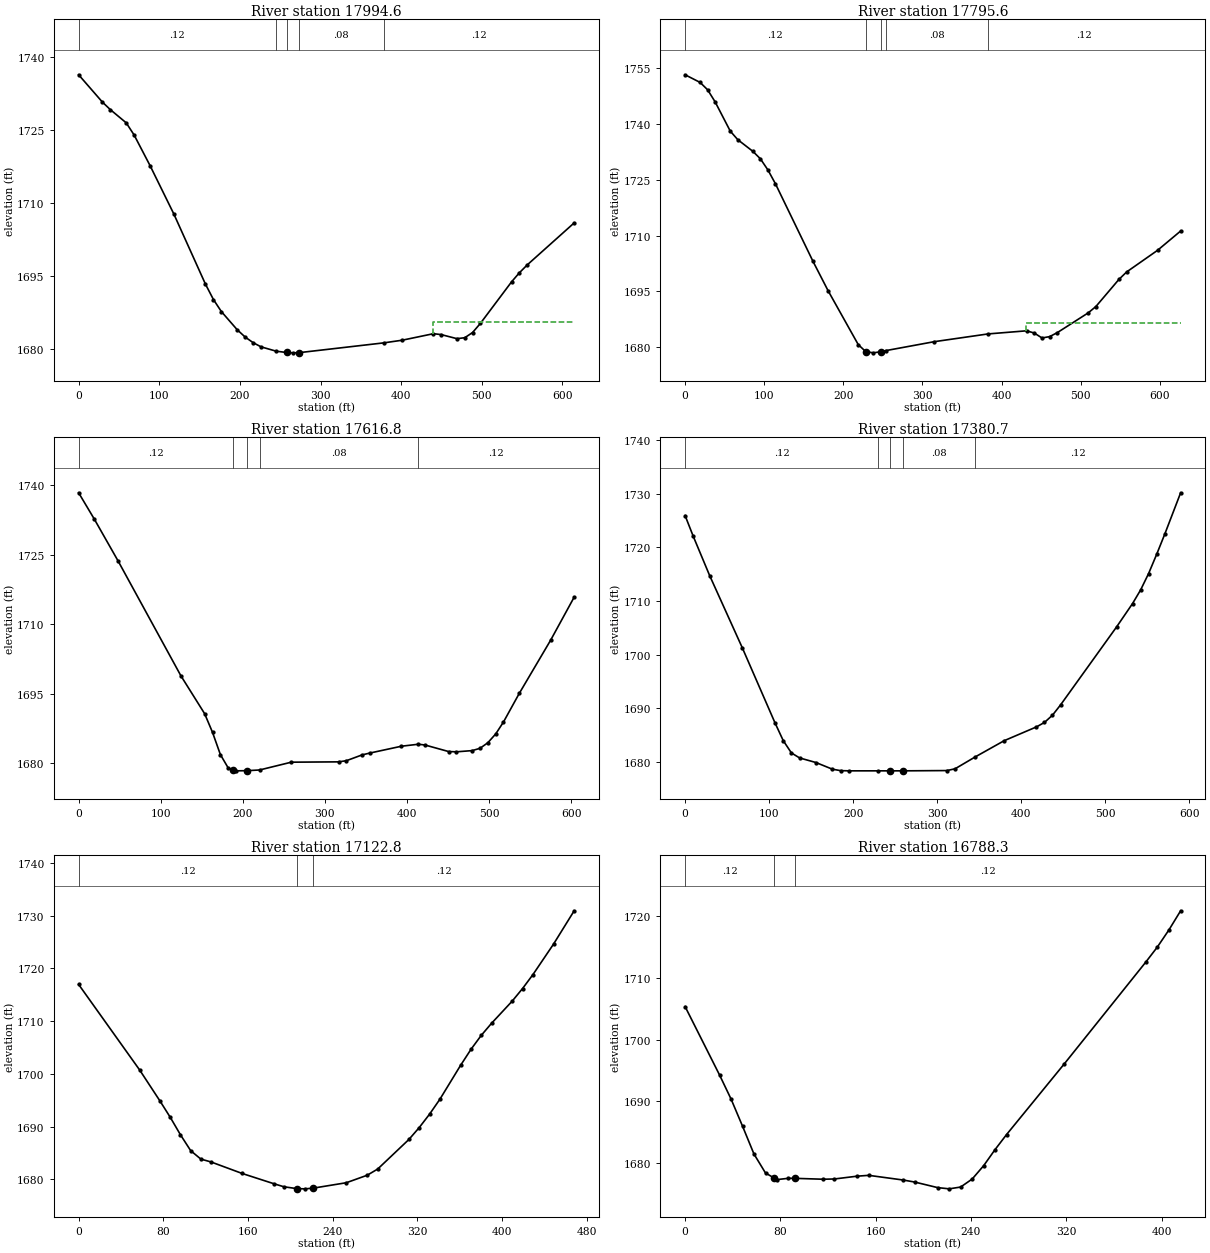
Type RM Length L Ch R = 1 ,17994.6 ,197.6,199,200.2
XS GIS Cut Line= 3
     1836586.778      211809.862     1836850.344      211778.076
     1837196.196      211731.193
#Sta/Elev= 30
       0 1736.32    29.5 1730.71    39.3 1729.17      59 1726.46    68.8 1723.96
    88.5  1717.7     118 1707.77   157.3 1693.34   167.2 1690.18     177 1687.72
   196.6    1684   206.5 1682.49   216.3 1681.35   226.2 1680.48  245.011679.588
     258 1679.32   265.5 1679.25     273 1679.28  378.311681.294   401.2 1681.84
     440 1683.18   449.7 1682.99   469.1 1682.16   478.8 1682.35   488.5 1683.42
   498.2 1685.29   536.9 1693.83   546.6 1695.69   556.3  1697.3   614.5 1705.92
#Mann= 5 ,-1 , 0
       0     .12       0  245.01     .08       0     258    .045       0
     273     .08       0  378.31     .12       0
#XS Ineff= 2 , 0
                          439.22         1685.49
Permanent Ineff=
       F       F
Bank Sta=258,273
XS Rating Curve= 0 ,0
Exp/Cntr=0.3,0.1

Type RM Length L Ch R = 1 ,17795.6 ,172.9,178.8,182.9
XS GIS Cut Line= 3
     1836586.267        211960.8     1836861.738       211945.83
     1837211.821      211930.916
#Sta/Elev= 30
       0 1753.27      19 1751.21    28.5 1749.22      38 1745.96    57.1  1738.1
    66.6  1735.8    85.6 1732.67    95.1 1730.67   104.6 1727.68   114.2 1723.93
   161.7 1703.03   180.8 1695.12   218.8 1680.66   228.3 1678.76   237.8 1678.43
   247.3 1678.72   253.5 1679.02   314.8 1681.43  383.031683.523   431.6 1684.36
   441.3 1683.76   451.1 1682.43   460.8  1682.8   470.5 1683.88   509.5 1689.19
   519.2  1690.9   548.4 1698.22   558.1 1700.21   597.1 1706.02   626.3 1711.22
#Mann= 5 ,-1 , 0
       0     .12       0   228.3    .045       0   247.3     .12       0
   253.5     .08       0  383.03     .12       0
#XS Ineff= 2 , 0
                          430.55         1686.57
Permanent Ineff=
       F       F
Bank Sta=228.3,247.3
XS Rating Curve= 0 ,0
Exp/Cntr=0.3,0.1

Type RM Length L Ch R = 1 ,17616.8 ,234.8,236.1,236.5
XS GIS Cut Line= 3
     1836625.131      212080.789     1836994.923       212138.08
     1837220.617      212096.414
#Sta/Elev= 30
       0 1738.38    19.2 1732.66      48 1723.67   124.7  1698.8   153.5 1690.65
   163.1 1686.62   172.7 1681.81   182.3  1678.9  188.041678.541   191.9  1678.3
  205.431678.338  220.451678.486   259.1 1680.17   316.6 1680.24   326.2 1680.49
   345.4 1681.75     355 1682.15   393.3 1683.62  413.931684.048     422 1683.88
   450.7 1682.47   460.3 1682.41   479.4 1682.67     489 1683.17   498.5 1684.37
   508.1 1686.27   517.6 1688.86   536.8 1695.03     575 1706.52   603.7 1715.83
#Mann= 5 ,-1 , 0
       0     .12       0  188.04    .045       0  205.43     .12       0
  220.45     .08       0  413.93     .12       0
Bank Sta=188.04,205.43
XS Rating Curve= 0 ,0
Exp/Cntr=0.3,0.1

Type RM Length L Ch R = 1 ,17380.7 ,258.2,257.9,269.5
XS GIS Cut Line= 3
     1836611.242      212297.802      1837005.34      212360.302
     1837132.076      212502.664
#Sta/Elev= 30
       0 1725.95     9.7 1722.08    29.2 1714.76    68.1 1701.27     107 1687.27
   116.8 1683.96   126.5 1681.67   136.2 1680.74   155.7 1679.88   175.2 1678.64
   184.9 1678.37   194.6 1678.33  229.52 1678.33   243.7 1678.33   258.7 1678.33
   311.4 1678.38   321.2 1678.71  344.911680.902   379.6 1683.95   418.1 1686.53
   427.6 1687.36   437.1 1688.71   446.7 1690.62   513.4 1705.18   532.4 1709.54
     542 1712.08   551.5 1715.14     561 1718.69   570.6 1722.44   589.6  1730.2
#Mann= 5 ,-1 , 0
       0     .12       0  229.52     .08       0   243.7    .045       0
   258.7     .08       0  344.91     .12       0
Bank Sta=243.7,258.7
XS Rating Curve= 0 ,0
Exp/Cntr=0.3,0.1

Type RM Length L Ch R = 1 ,17122.8 ,319.1,334.5,290.5
XS GIS Cut Line= 4
     1836581.728      212492.247     1836691.103      212553.011
     1836875.131      212585.997     1837000.131      212679.747
#Sta/Elev= 30
       0 1716.96    57.8  1700.7      77 1694.82    86.6 1691.76    96.2 1688.46
   105.9 1685.44   115.5 1683.84   125.1  1683.3   154.6 1681.11   184.2 1679.19
     194 1678.59   206.3 1678.24   213.7  1678.2   221.3 1678.32     253 1679.36
   272.7 1680.78   282.6 1681.95   312.1 1687.56   321.8  1689.8   331.6 1692.35
   341.4 1695.19   360.9  1701.6   370.7 1704.63   380.4 1707.28   390.2 1709.59
   409.7 1713.79   419.5 1716.18   429.3 1718.82   448.8 1724.61   468.3 1730.93
#Mann= 3 ,-1 , 0
       0     .12       0   206.3    .045       0   221.3     .12       0
Bank Sta=206.3,221.3
XS Rating Curve= 0 ,0
Exp/Cntr=0.3,0.1

Type RM Length L Ch R = 1 ,16788.3 ,367.9,378.6,411.2
XS GIS Cut Line= 3
      1836514.02      212657.177      1836764.02      212782.177
     1836895.965        212816.9
#Sta/Elev= 28
       0 1705.37    28.9 1694.27    38.6 1690.35    48.2 1685.96    57.8 1681.44
    67.5 1678.35   74.681677.548    77.1 1677.28    86.7 1677.49   92.371677.484
   115.7 1677.34   125.3 1677.38   144.6 1677.84   154.2 1677.97   183.1 1677.21
   192.8 1676.88     212 1675.98   221.7 1675.78   231.3 1676.07     241 1677.37
   250.6 1679.53   260.2 1682.15   269.9  1684.6   318.5 1696.11   386.7 1712.58
   396.4 1715.02   406.2 1717.82     416 1720.92
#Mann= 3 ,-1 , 0
       0     .12       0   74.68    .045       0   92.37     .12       0
Bank Sta=74.68,92.37
XS Rating Curve= 0 ,0
Exp/Cntr=0.3,0.1

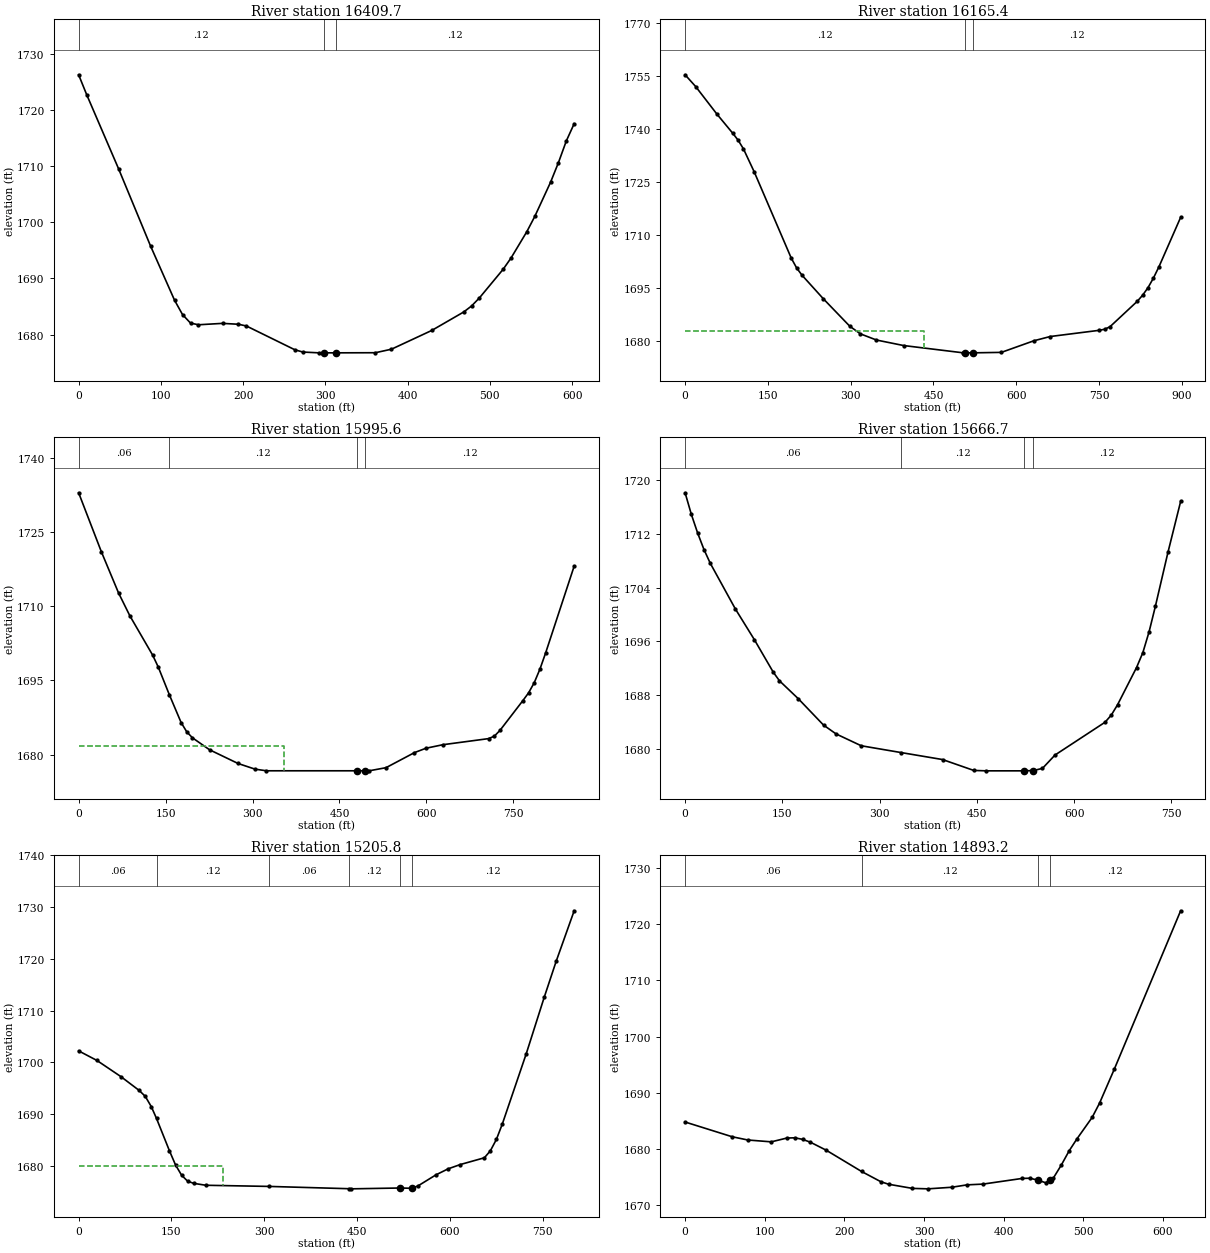
Type RM Length L Ch R = 1 ,16409.7 ,239.9,244.3,222.9
XS GIS Cut Line= 4
     1836345.617      212730.094      1836482.77      212881.136
     1836715.409      212957.525     1836866.451      212929.747
#Sta/Elev= 30
       0 1726.36     9.7 1722.84    48.6 1709.57    87.4 1695.81   116.6 1686.12
   126.3 1683.56     136 1682.04   145.7 1681.74   174.9 1681.99   194.3 1681.83
     204 1681.52   262.8 1677.28   272.6 1676.87   292.2 1676.73   298.2 1676.73
   313.2 1676.73   360.7 1676.75   380.3 1677.38   429.3 1680.73   468.1 1684.02
   477.7  1685.1   487.3 1686.55   516.1 1691.65   525.7 1693.67   544.9 1698.37
   554.5 1701.07   573.7 1707.18   583.3 1710.69   592.9 1714.57   602.4 1717.63
#Mann= 3 ,-1 , 0
       0     .12       0   298.2    .045       0   313.2     .12       0
Bank Sta=298.2,313.2
XS Rating Curve= 0 ,0
Exp/Cntr=0.3,0.1

Type RM Length L Ch R = 1 ,16165.4 ,203.2,169.8,148.3
XS GIS Cut Line= 3
     1836053.083      212952.316     1836339.541        213129.4
     1836886.416        213004.4
#Sta/Elev= 30
       0 1755.42    19.2 1752.08    57.7 1744.28    86.6 1738.82    96.2 1736.88
   105.8 1734.42   125.1 1727.99   192.4 1703.51   202.1 1700.75   211.7 1698.72
   250.2 1692.07   298.3 1684.27   317.5 1682.11   346.6 1680.36   395.8  1678.8
   504.1 1676.73   506.4 1676.73   521.4 1676.73     573 1676.86     632 1680.15
   661.6 1681.35   750.1  1683.1     760  1683.4   769.8 1684.12     819 1691.28
   828.9 1693.03   838.7 1695.18   848.5 1697.89   858.4 1701.05   897.8 1715.07
#Mann= 3 ,-1 , 0
       0     .12       0   506.4    .045       0   521.4     .12       0
#XS Ineff= 2 , 0
          433.44 1682.97
Permanent Ineff=
       F       F
Bank Sta=506.4,521.4
XS Rating Curve= 0 ,0
Exp/Cntr=0.3,0.1

Type RM Length L Ch R = 1 ,15995.6 ,265.6,328.9,296.3
XS GIS Cut Line= 3
     1836437.848      213650.667     1836675.695      213079.487
     1836904.862      213022.195
#Sta/Elev= 30
       0 1732.98    39.3 1721.02    68.8 1712.73    88.4 1708.08   127.7 1700.13
   137.5 1697.69  156.73 1692.05   176.8 1686.49   186.6  1684.6   196.4  1683.4
   225.9 1680.98     275 1678.21   304.4 1677.06   324.1 1676.73   479.7 1676.73
   494.7 1676.73   500.9 1676.72   530.3 1677.36   579.4 1680.41   599.1 1681.29
   628.6 1682.01   707.3 1683.24   717.2 1683.74     727 1684.92   766.4 1690.93
   776.2 1692.49     786 1694.55   795.9 1697.32   805.7 1700.59   854.9 1718.14
#Mann= 4 ,-1 , 0
       0     .06       0  156.73     .12       0   479.7    .045       0
   494.7     .12       0
#XS Ineff= 2 , 0
          353.97 1681.82
Permanent Ineff=
       F       F
Bank Sta=479.7,494.7
XS Rating Curve= 0 ,0
Exp/Cntr=0.3,0.1

Type RM Length L Ch R = 1 ,15666.7 ,517.4,460.9,461
XS GIS Cut Line= 4
     1836493.187      213655.441     1836736.242      213533.914
     1836862.978      213190.164     1836970.617      213124.191
#Sta/Elev= 30
       0 1718.09     9.7 1714.86    19.4 1712.09    29.1 1709.65    38.8 1707.61
    77.6  1700.8   106.8 1696.25   135.9 1691.42   145.6 1690.12   174.7 1687.45
   213.5 1683.54   232.9 1682.22   271.7 1680.46  333.511679.443   397.1 1678.41
   445.3 1676.79   464.6 1676.73   522.3 1676.73   537.3 1676.77   551.3  1677.1
   570.6 1679.08   647.8 1683.96   657.5 1685.03   667.2 1686.58   696.4  1692.1
   706.1 1694.31   715.8 1697.44   725.5 1701.23   744.9 1709.26   764.4  1716.8
#Mann= 4 ,-1 , 0
       0     .06       0  333.51     .12       0   522.3    .045       0
   537.3     .12       0
Bank Sta=522.3,537.3
XS Rating Curve= 0 ,0
Exp/Cntr=0.3,0.1

Type RM Length L Ch R = 1 ,15205.8 ,311.8,312.6,313.4
XS GIS Cut Line= 3
     1836918.534      214006.787     1837206.728      213428.662
     1837316.103      213319.287
#Sta/Elev= 30
       0 1702.24    29.4  1700.4    68.5 1697.25    97.9 1694.59   107.7 1693.45
   117.4 1691.47  125.841689.188   146.8 1682.92   156.6  1680.2   166.4 1678.22
   176.2 1677.06     186 1676.65   205.5 1676.28  308.071676.056  436.981675.614
   440.4 1675.59   518.7 1675.75   538.3  1675.7   548.1 1676.14   577.5  1678.3
     597 1679.45   616.6 1680.28   655.6 1681.59   665.3 1682.94     675 1685.13
   684.6 1688.11   723.3  1701.7   752.3 1712.59   771.6 1719.54   800.7  1729.3
#Mann= 6 ,-1 , 0
       0     .06       0  125.84     .12       0  308.07     .06       0
  436.98     .12       0   518.7    .045       0   538.3     .12       0
#XS Ineff= 2 , 0
          233.23 1679.93
Permanent Ineff=
       F       F
Bank Sta=518.7,538.3
XS Rating Curve= 0 ,0
Exp/Cntr=0.3,0.1

Type RM Length L Ch R = 1 ,14893.2 ,421.5,420.4,418.7
XS GIS Cut Line= 3
     1837203.256      214096.414      1837442.84      213655.441
     1837527.909      213570.372
#Sta/Elev= 30
       0  1684.8      59 1682.18    78.7  1681.6   108.2 1681.27   127.9 1681.95
   137.8 1681.99   147.6 1681.71   157.4  1681.2   177.1 1679.79  221.591675.999
     246 1674.16   255.8 1673.72   285.4 1672.99     305 1672.91   334.6 1673.19
   354.2 1673.62   373.9 1673.75   423.1 1674.76     433  1674.8   442.8 1674.46
   452.6    1674  457.561674.428   462.5 1674.86   472.3 1677.12   482.2 1679.67
     492  1681.8   511.1 1685.62   520.4 1688.16   538.9  1694.2   622.2 1722.38
#Mann= 4 ,-1 , 0
       0     .06       0  221.59     .12       0   442.8    .045       0
  457.56     .12       0
Bank Sta=442.8,457.56
XS Rating Curve= 0 ,0
Exp/Cntr=0.3,0.1

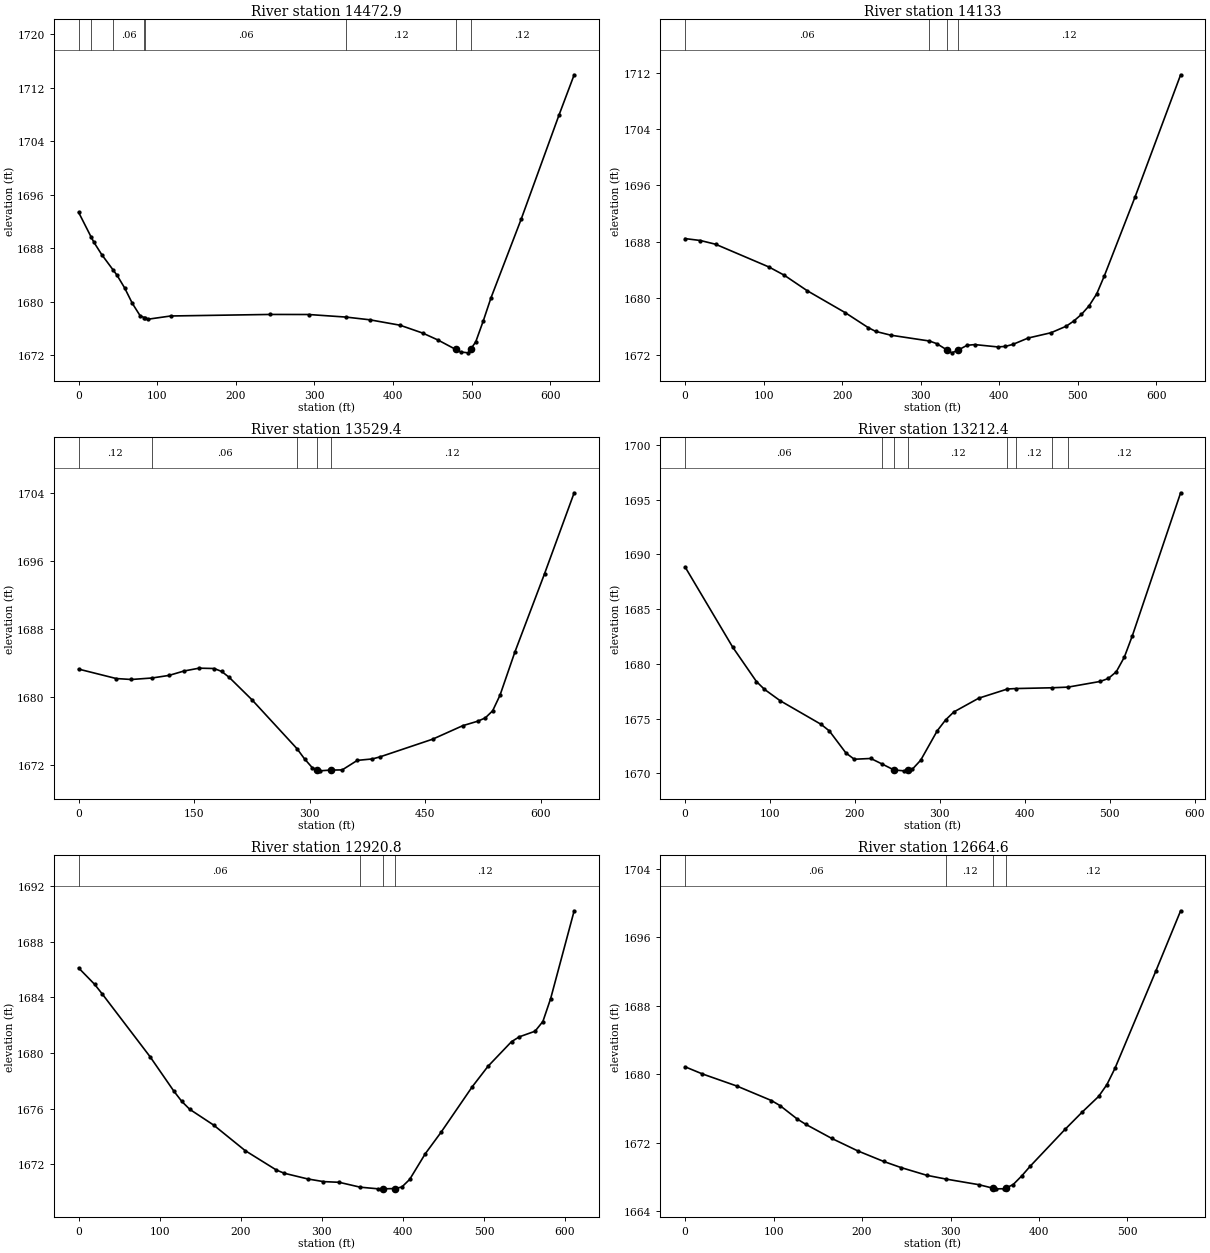
Type RM Length L Ch R = 1 ,14472.9 ,296.5,339.8,335.6
XS GIS Cut Line= 3
     1837487.978      214292.594     1837720.617      214042.594
     1837842.145      213780.441
#Sta/Elev= 30
       0 1693.39   15.651689.763    19.5 1688.91    29.3 1687.09   44.221684.724
    48.8    1684    58.5  1682.1    68.3 1679.79    78.1 1677.96   83.74 1677.64
    84.91677.574    87.8 1677.41   117.1  1677.9   243.9 1678.13   292.7 1678.12
  340.311677.734   370.4 1677.33   408.9 1676.52   437.8 1675.34   457.1 1674.31
  479.671672.902     486 1672.52   495.6 1672.39  498.761672.935   505.2 1674.04
   514.9 1677.21   524.5 1680.59     563 1692.38   611.2 1707.97   630.4 1713.96
#Mann= 8 ,-1 , 0
       0     .06       0   15.65    .016       0   44.22     .06       0
   83.74     .12       0    84.9     .06       0  340.31     .12       0
  479.67    .045       0  498.76     .12       0
Bank Sta=479.67,498.76
XS Rating Curve= 0 ,0
Exp/Cntr=0.3,0.1

Type RM Length L Ch R = 1 ,14133   ,558.8,603.6,555.4
XS GIS Cut Line= 2
     1837769.228      214428.011     1838033.117      213855.094
#Sta/Elev= 30
       0 1688.46    19.4 1688.19    38.8 1687.66   106.8 1684.43   126.2 1683.27
   155.3 1681.08   203.8 1677.96   232.9 1675.85   242.6  1675.3     262 1674.76
   311.11673.936   320.2 1673.57  333.991672.629   339.6 1672.26     347 1672.62
     359 1673.33   368.8 1673.43   397.9  1673.1   407.6 1673.17   417.3 1673.46
   436.7 1674.36   465.8 1675.11   485.2 1676.04   494.9 1676.78   504.6 1677.72
   514.3 1678.93     524 1680.63   533.7 1683.18   572.6 1694.31   630.8 1711.69
#Mann= 4 ,-1 , 0
       0     .06       0   311.1     .12       0  333.99    .045       0
     347     .12       0
Bank Sta=333.99,347
XS Rating Curve= 0 ,0
Exp/Cntr=0.3,0.1

Type RM Length L Ch R = 1 ,13529.4 ,316.8,317,315.4
XS GIS Cut Line= 3
     1838121.659       214535.65     1838222.353      214026.969
     1838283.117      213917.594
#Sta/Elev= 30
       0 1683.32    48.9 1682.21    68.5  1682.1   95.361682.275   117.4 1682.58
     137  1683.1   156.5 1683.43   176.1 1683.39   185.9 1683.04   195.7 1682.34
     225 1679.73  283.581673.972   293.5 1672.76   303.3 1671.75  310.081671.477
   313.1 1671.36  327.221671.448   342.4 1671.47     362 1672.59   381.6 1672.76
   391.4    1673   459.8 1675.08     499 1676.67   518.6  1677.2   528.2 1677.58
   537.8 1678.42   547.4 1680.26   566.7 1685.33   605.2 1694.53   643.7 1704.05
#Mann= 5 ,-1 , 0
       0     .12       0   95.36     .06       0  283.58     .12       0
  310.08    .045       0  327.22     .12       0
Bank Sta=310.08,327.22
XS Rating Curve= 0 ,0
Exp/Cntr=0.3,0.1

Type RM Length L Ch R = 1 ,13212.4 ,301,291.6,279.2
XS GIS Cut Line= 4
     1838477.562      214518.289     1838453.256      214389.816
     1838491.451      214148.497     1838444.576      213945.372
#Sta/Elev= 30
       0 1688.86      56 1681.54      84 1678.39    93.4 1677.68   112.1 1676.63
   160.1 1674.48   169.8 1673.88   189.4 1671.86   199.2 1671.29   218.7 1671.36
  231.571670.868  246.031670.308   257.8 1670.23  262.951670.309   267.6 1670.38
   277.4  1671.2   296.9 1673.89   306.7 1674.88   316.4 1675.61   345.8 1676.87
  379.561677.708  389.51 1677.75  431.65 1677.82  450.82 1677.88   488.8  1678.4
   498.3 1678.67   507.7 1679.28   517.2 1680.62   526.7 1682.59   583.5 1695.64
#Mann= 8 ,-1 , 0
       0     .06       0  231.57     .12       0  246.03    .045       0
  262.95     .12       0  379.56     .06       0  389.51     .12       0
  431.65     .06       0  450.82     .12       0
Bank Sta=246.03,262.95
XS Rating Curve= 0 ,0
Exp/Cntr=0.3,0.1

Type RM Length L Ch R = 1 ,12920.8 ,240.1,256.2,272.6
XS GIS Cut Line= 3
      1838639.02      214518.289     1838722.353      214341.205
     1838626.867      213936.691
#Sta/Elev= 30
       0 1686.11    19.6 1684.94    29.4 1684.22    88.1 1679.73   117.4 1677.26
   127.2 1676.52     137 1675.95   166.4 1674.82   205.4 1672.98     244 1671.58
   253.7 1671.35   282.7 1670.94     302 1670.75   321.4  1670.7  347.321670.349
   369.7 1670.23   375.1 1670.23   390.1 1670.25   398.7 1670.36   408.4 1670.91
   427.7 1672.76     447 1674.29   485.7 1677.58     505 1679.04     534 1680.81
   543.7 1681.16     563 1681.56   572.7 1682.26   582.3 1683.91   611.3 1690.22
#Mann= 4 ,-1 , 0
       0     .06       0  347.32     .12       0   375.1    .045       0
   390.1     .12       0
Bank Sta=375.1,390.1
XS Rating Curve= 0 ,0
Exp/Cntr=0.3,0.1

Type RM Length L Ch R = 1 ,12664.6 ,202.1,203.8,204.4
XS GIS Cut Line= 3
     1838739.715      214506.136     1838948.048      214108.566
     1839040.062      214046.066
#Sta/Elev= 28
       0 1680.86    19.5 1680.03    58.6 1678.61    97.6 1676.92   107.3 1676.33
   126.8 1674.76   136.6 1674.13   165.9 1672.49   195.2 1671.04   224.4 1669.81
   243.9  1669.1   273.2 1668.19   295.11667.746   331.8  1667.1  348.081666.685
   351.3 1666.61     361 1666.62  362.651666.703   370.8 1667.11   380.5 1668.12
   390.3 1669.28   429.3 1673.54   448.8 1675.57   467.4  1677.4   476.7 1678.77
   485.9 1680.69   532.3  1692.1   560.1 1699.08
#Mann= 4 ,-1 , 0
       0     .06       0   295.1     .12       0  348.08    .045       0
  362.65     .12       0
Bank Sta=348.08,362.65
XS Rating Curve= 0 ,0
Exp/Cntr=0.3,0.1

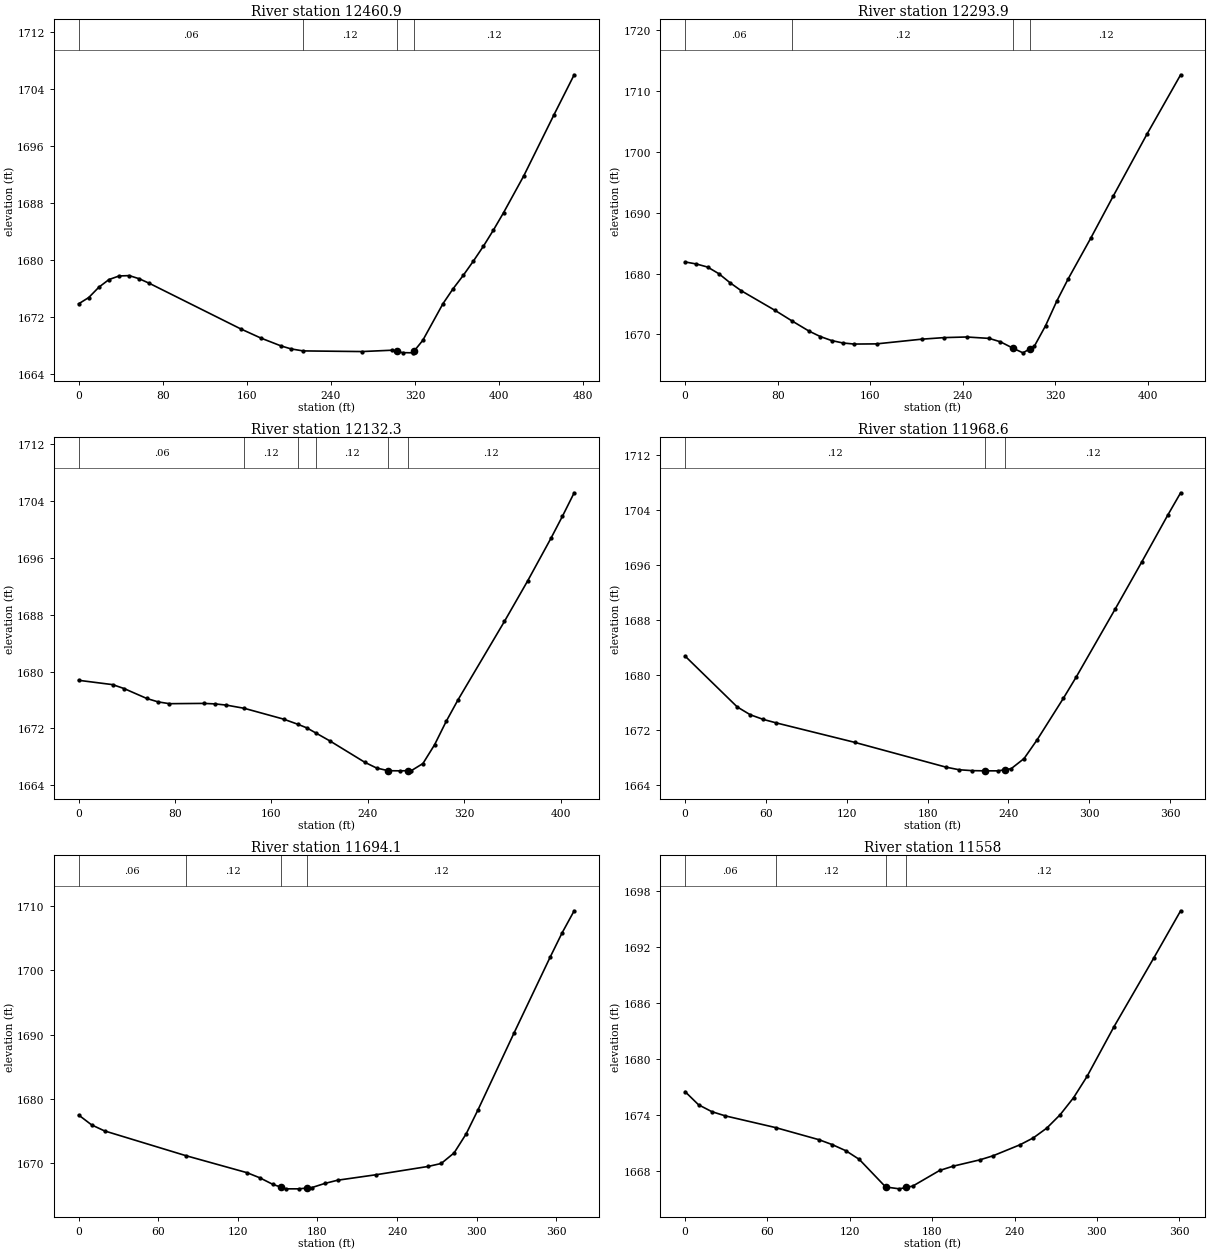
Type RM Length L Ch R = 1 ,12460.9 ,167,167,167.3
XS GIS Cut Line= 3
      1838920.27      214551.275      1839107.77      214237.039
     1839184.159      214164.122
#Sta/Elev= 30
       0 1673.83     9.6 1674.71    19.3 1676.17    28.9 1677.24    38.5 1677.74
    48.2 1677.79    57.8 1677.34    67.4  1676.7   154.1 1670.32   173.3 1669.03
   192.6 1667.92   202.2  1667.5  213.541667.222   269.6 1667.13   298.5 1667.32
  302.47 1667.18   308.2 1666.98   317.8 1666.95  318.961667.161   327.4 1668.69
   346.7 1673.86   356.3 1675.95   365.9 1677.81   375.5 1679.81   385.1 1681.91
   394.7 1684.19   404.3 1686.62   423.5 1691.78   452.3 1700.37   471.5 1705.98
#Mann= 4 ,-1 , 0
       0     .06       0  213.54     .12       0  302.47    .045       0
  318.96     .12       0
Bank Sta=302.47,318.96
XS Rating Curve= 0 ,0
Exp/Cntr=0.3,0.1

Type RM Length L Ch R = 1 ,12293.9 ,162.9,161.6,160
XS GIS Cut Line= 2
     1839066.103      214627.664     1839288.326      214261.344
#Sta/Elev= 30
       0  1681.9     9.7 1681.57    19.5 1681.06    29.2 1679.97      39 1678.47
    48.7 1677.16    77.9 1673.94   92.29 1672.24   107.1 1670.56   116.8 1669.67
   126.6 1669.01   136.3 1668.61   146.1 1668.43   165.5 1668.46   204.5 1669.23
     224 1669.49   243.4 1669.59   262.9 1669.36   272.6  1668.8   283.81667.718
   292.1 1666.99  298.461667.694   301.9 1668.07   311.6 1671.43   321.3 1675.47
   331.1  1679.1   350.6 1685.77     370 1692.66   399.2 1702.84   428.4 1712.61
#Mann= 4 ,-1 , 0
       0     .06       0   92.29     .12       0   283.8    .045       0
  298.46     .12       0
Bank Sta=283.8,298.46
XS Rating Curve= 0 ,0
Exp/Cntr=0.3,0.1

Type RM Length L Ch R = 1 ,12132.3 ,172.1,163.7,154.2
XS GIS Cut Line= 3
     1839310.895      214728.358     1839297.006      214568.636
     1839413.326      214346.414
#Sta/Elev= 30
       0 1678.77    28.3 1678.16    37.7 1677.61    56.6 1676.21      66 1675.73
    75.4 1675.48   103.7 1675.52   113.2 1675.45   122.6 1675.28  137.42 1674.83
     170 1673.31  181.941672.581   189.3 1672.08  196.581671.382   208.6 1670.23
   237.5 1667.23   247.2 1666.43   256.8 1666.05   266.4 1666.03  273.571666.052
   276.1 1666.06   285.7 1667.06   295.4 1669.71     305 1672.99   314.7 1675.99
   353.3 1687.05   372.6 1692.76   391.9 1698.75   401.5 1701.87   411.2 1705.16
#Mann= 6 ,-1 , 0
       0     .06       0  137.42     .12       0  181.94     .06       0
  196.58     .12       0   256.8    .045       0  273.57     .12       0
Bank Sta=256.8,273.57
XS Rating Curve= 0 ,0
Exp/Cntr=0.3,0.1

Type RM Length L Ch R = 1 ,11968.6 ,282.5,274.5,265.3
XS GIS Cut Line= 2
     1839484.506      214738.775     1839517.492      214372.455
#Sta/Elev= 21
       0 1682.73    38.7 1675.33    48.4 1674.19    58.1 1673.51    67.8    1673
   125.8 1670.18   193.6 1666.57   203.3 1666.19   212.9 1666.06   222.6 1666.03
   232.3 1666.03  237.491666.198     242 1666.34   251.6 1667.82   261.3 1670.55
   280.7 1676.57   290.4 1679.72   319.4 1689.64   338.8 1696.38   358.1  1703.2
   367.8  1706.5
#Mann= 3 ,-1 , 0
       0     .12       0   222.6    .045       0  237.49     .12       0
Bank Sta=222.6,237.49
XS Rating Curve= 0 ,0
Exp/Cntr=0.3,0.1

Type RM Length L Ch R = 1 ,11694.1 ,134.3,136.1,136.9
XS GIS Cut Line= 3
     1839739.715       214731.83     1839677.215      214455.789
     1839672.006      214365.511
#Sta/Elev= 24
       0 1677.52     9.8 1675.98    19.5 1675.05   80.761671.207   126.9 1668.56
   136.6 1667.76   146.4 1666.74  152.591666.305   156.2 1666.05   165.9 1666.05
  172.02 1666.17   175.7 1666.24   185.4 1666.88   195.2 1667.39   224.5 1668.25
   263.5 1669.53   273.3 1669.99     283 1671.63   292.1 1674.59   301.1 1678.36
   328.2 1690.27   355.4 1702.04   364.4 1705.81   373.5 1709.24
#Mann= 4 ,-1 , 0
       0     .06       0   80.76     .12       0  152.59    .045       0
  172.02     .12       0
Bank Sta=152.59,172.02
XS Rating Curve= 0 ,0
Exp/Cntr=0.3,0.1

Type RM Length L Ch R = 1 ,11558   ,185.5,177.8,169.4
XS GIS Cut Line= 2
     1839862.978      214714.469     1839802.215      214358.566
#Sta/Elev= 26
       0 1676.51     9.8  1675.1    19.5 1674.36    29.3 1673.91   65.861672.656
    97.6 1671.35   107.3 1670.82   117.1 1670.17   126.9 1669.24   146.1 1666.28
   156.1 1666.08   161.1 1666.23   165.9 1666.38   185.4 1668.05   195.2 1668.51
   214.7 1669.19   224.4 1669.63     244 1670.81   253.7 1671.55   263.5  1672.6
   273.2 1674.03     283 1675.86   292.8 1678.14   312.3 1683.44   341.5 1690.87
     361 1695.92
#Mann= 4 ,-1 , 0
       0     .06       0   65.86     .12       0   146.1    .045       0
   161.1     .12       0
Bank Sta=146.1,161.1
XS Rating Curve= 0 ,0
Exp/Cntr=0.3,0.1

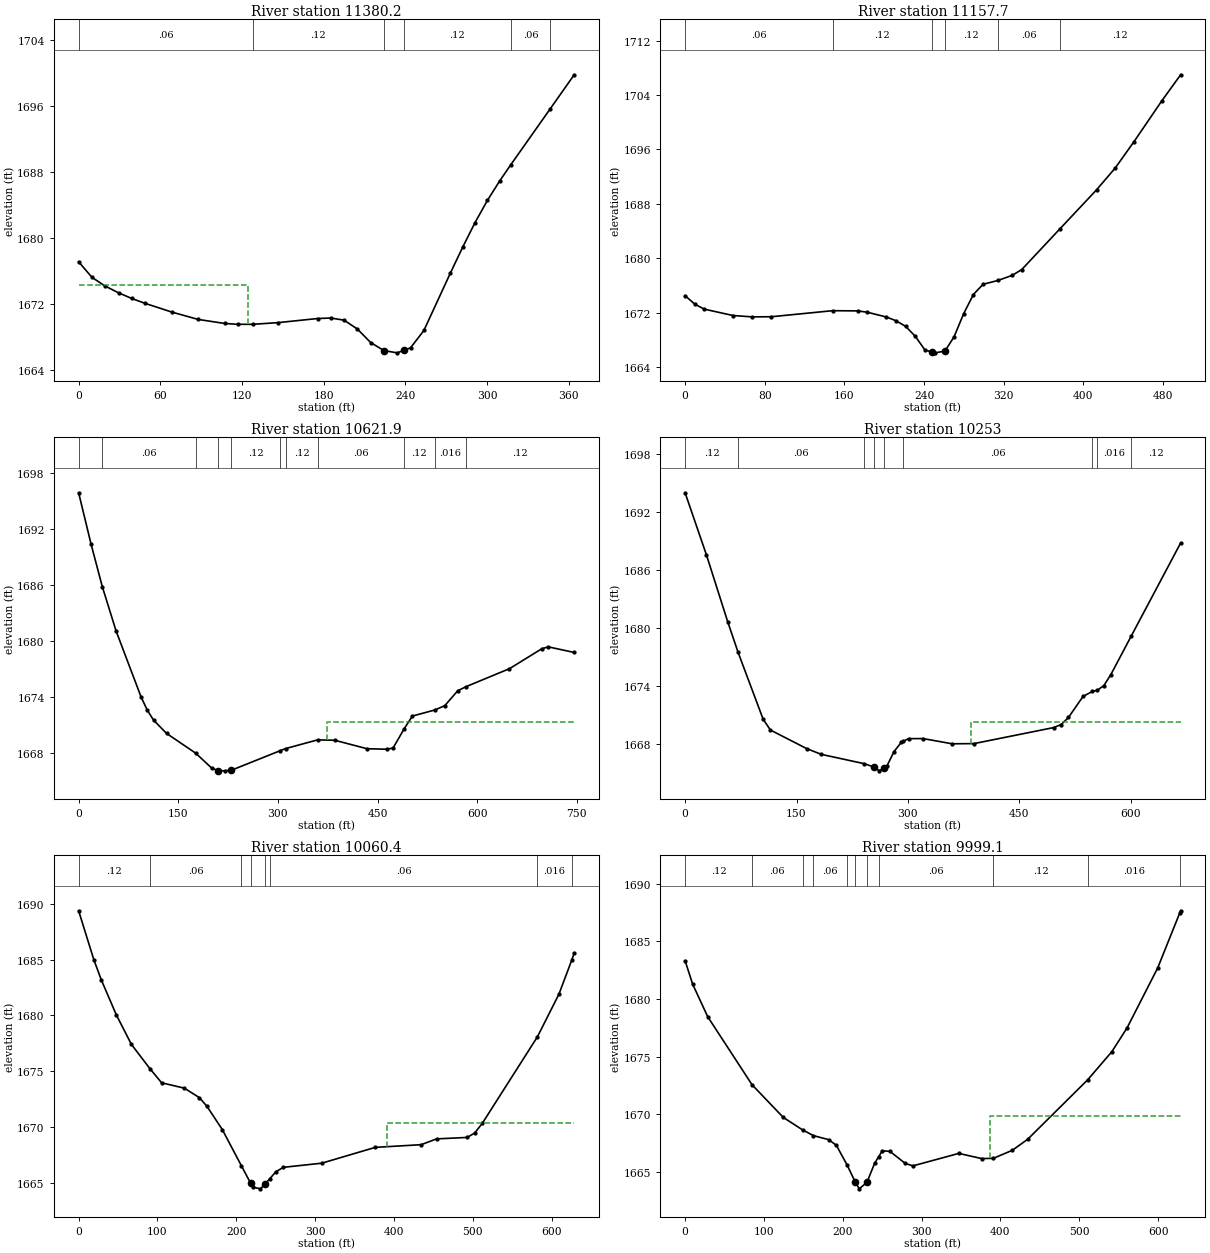
Type RM Length L Ch R = 1 ,11380.2 ,216.4,222.6,228.3
XS GIS Cut Line= 3
     1840078.256      214650.233     1839941.103      214414.122
      1839920.27       214325.58
#Sta/Elev= 30
       0 1677.08     9.8 1675.19    19.5 1674.13    29.3 1673.32      39 1672.63
    48.8 1672.04    68.3 1670.99    87.8 1670.09   107.3  1669.6     117  1669.5
   127.91669.498   146.3  1669.7   175.5  1670.2   185.3 1670.26     195    1670
   204.8 1668.92   214.5 1667.29   224.3 1666.31     234 1666.04  238.731666.333
   243.8 1666.65   253.6 1668.75   273.1 1675.72   282.2 1678.88   291.2 1681.84
   300.3 1684.53   309.4 1686.91  317.411688.838  346.31  1695.6     364 1699.75
#Mann= 6 ,-1 , 0
       0     .06       0   127.9     .12       0   224.3    .045       0
  238.73     .12       0  317.41     .06       0  346.31     .12       0
#XS Ineff= 2 , 0
          124.25 1674.22
Permanent Ineff=
       F       F
Bank Sta=224.3,238.73
XS Rating Curve= 0 ,0
Exp/Cntr=0.3,0.1

Type RM Length L Ch R = 1 ,11157.7 ,510,535.8,562.9
XS GIS Cut Line= 4
      1840139.02      214646.761     1840189.367      214460.997
     1840151.173      214320.372      1840014.02      214238.775
#Sta/Elev= 30
       0  1674.5     9.6 1673.27    19.2 1672.52    48.1 1671.58    67.4 1671.38
    86.6  1671.4  148.141672.289   173.2 1672.26   182.8 1672.07   202.2 1671.36
   211.9 1670.81   221.6 1669.98   231.3 1668.51     241  1666.5  247.911666.211
   250.8 1666.09  260.961666.335   270.2 1668.45   279.9 1671.87   289.6 1674.67
   299.3 1676.17  314.241676.735   328.5 1677.48   338.2 1678.34  376.241684.284
   413.3 1690.06   432.1 1693.28   450.8 1697.12     479 1703.18   497.8 1706.99
#Mann= 6 ,-1 , 0
       0     .06       0  148.14     .12       0  247.91    .045       0
  260.96     .12       0  314.24     .06       0  376.24     .12       0
Bank Sta=247.91,260.96
XS Rating Curve= 0 ,0
Exp/Cntr=0.3,0.1

Type RM Length L Ch R = 1 ,10621.9 ,360.9,368.8,369.5
XS GIS Cut Line= 3
     1840269.228      214787.386     1840336.937      214697.108
     1840866.451      214349.886
#Sta/Elev= 30
       0 1695.87    18.8 1690.34   35.711685.781    56.4 1681.04      94 1673.97
   103.4 1672.54   112.8 1671.48   132.3 1670.06  176.281667.933   200.5 1666.32
   210.3 1666.07     220 1666.04   229.8  1666.1  303.611668.207  311.521668.426
  359.64 1669.36   385.6 1669.32   434.3 1668.41   463.6 1668.36   473.3 1668.48
  490.221670.568   502.5 1671.92  535.891672.561   551.2 1673.03   570.7 1674.63
  583.241675.071   648.6    1677   697.3 1679.14   707.1 1679.34     746 1678.74
#Mann= 11 ,-1 , 0
       0     .12       0   35.71     .06       0  176.28     .12       0
   210.3    .045       0   229.8     .12       0  303.61     .06       0
  311.52     .12       0  359.64     .06       0  490.22     .12       0
  535.89    .016       0  583.24     .12       0
#XS Ineff= 2 , 0
                          373.99         1671.33
Permanent Ineff=
       F       F
Bank Sta=210.3,229.8
XS Rating Curve= 0 ,0
Exp/Cntr=0.3,0.1

Type RM Length L Ch R = 1 ,10253   ,184.8,192.7,199.3
XS GIS Cut Line= 4
     1840369.923      214936.691      1840474.09      214922.802
      1840849.09      214710.997     1840977.562      214683.219
#Sta/Elev= 30
       0 1693.95    28.7 1687.55    57.3 1680.66   71.411677.476   105.1 1670.58
   114.9 1669.47   163.8 1667.55   183.4 1666.96  240.991666.002  253.991665.661
   261.7 1665.26  268.471665.578   271.5 1665.72   281.3 1667.25   291.1  1668.2
  294.011668.314   300.8 1668.58   320.4 1668.59   359.6 1668.05     389 1668.07
   496.6 1669.73   506.4 1670.04   516.2 1670.77   535.8 1672.94  548.371673.451
  555.121673.579   563.9 1674.06   573.3  1675.2  600.921679.201   667.2 1688.77
#Mann= 9 ,-1 , 0
       0     .12       0   71.41     .06       0  240.99     .12       0
  253.99    .045       0  268.47     .12       0  294.01     .06       0
  548.37     .12       0  555.12    .016       0  600.92     .12       0
#XS Ineff= 2 , 0
                          384.31         1670.27
Permanent Ineff=
       F       F
Bank Sta=253.99,268.47
XS Rating Curve= 0 ,0
Exp/Cntr=0.3,0.1

Type RM Length L Ch R = 1 ,10060.4 ,61.1,61.3,61
XS GIS Cut Line= 3
      1840380.34      215016.552     1840541.798      215037.386
     1841000.131      214954.052
#Sta/Elev= 30
       0 1689.39    19.2 1685.02    28.7  1683.2    47.9 1680.04      67  1677.4
   90.451675.229   105.3 1673.96   134.1 1673.48   153.2 1672.63   162.8 1671.85
   182.2 1669.77  206.341666.537  218.241664.943     221 1664.61   230.7 1664.45
  235.891664.841  242.191665.328   250.1 1665.98   259.8 1666.38   308.4 1666.75
   376.3 1668.17   434.5 1668.41     454 1668.93   492.8 1669.06   502.5 1669.46
   512.2 1670.34  581.991678.088   609.2  1681.9  625.411684.942   628.6 1685.59
#Mann= 8 ,-1 , 0
       0     .12       0   90.45     .06       0  206.34     .12       0
  218.24    .045       0  235.89     .12       0  242.19     .06       0
  581.99    .016       0  625.41     .12       0
#XS Ineff= 2 , 0
                          391.54         1670.39
Permanent Ineff=
       F       F
Bank Sta=218.24,235.89
XS Rating Curve= 0 ,0
Exp/Cntr=0.3,0.1

Type RM Length L Ch R = 1 ,9999.1  ,123.5,126.1,128.2
XS GIS Cut Line= 3
     1840392.492       215075.58     1840553.951      215096.414
     1841012.284       215013.08
#Sta/Elev= 30
       0 1683.31     9.6 1681.28    28.7 1678.46   84.971672.564   124.5 1669.74
  148.981668.659  162.84 1668.16   182.2 1667.81   191.9 1667.32  205.241665.651
  215.971664.125     221 1663.55   230.7 1664.12   240.4 1665.76  245.471666.324
   250.1 1666.84   259.8  1666.8   279.3 1665.75     289 1665.54   347.2 1666.62
   376.3 1666.17  391.071666.193   415.1 1666.89   434.5 1667.84   510.81673.005
   541.3 1675.43   560.7  1677.5   599.5 1682.69  627.251687.412   628.6 1687.64
#Mann= 11 ,-1 , 0
       0     .12       0   84.97     .06       0  148.98     .12       0
  162.84     .06       0  205.24     .12       0  215.97    .045       0
   230.7     .12       0  245.47     .06       0  391.07     .12       0
   510.8    .016       0  627.25     .12       0
#XS Ineff= 2 , 0
                           387.2         1669.88
Permanent Ineff=
       F       F
Bank Sta=215.97,230.7
XS Rating Curve= 0 ,0
Exp/Cntr=0.3,0.1