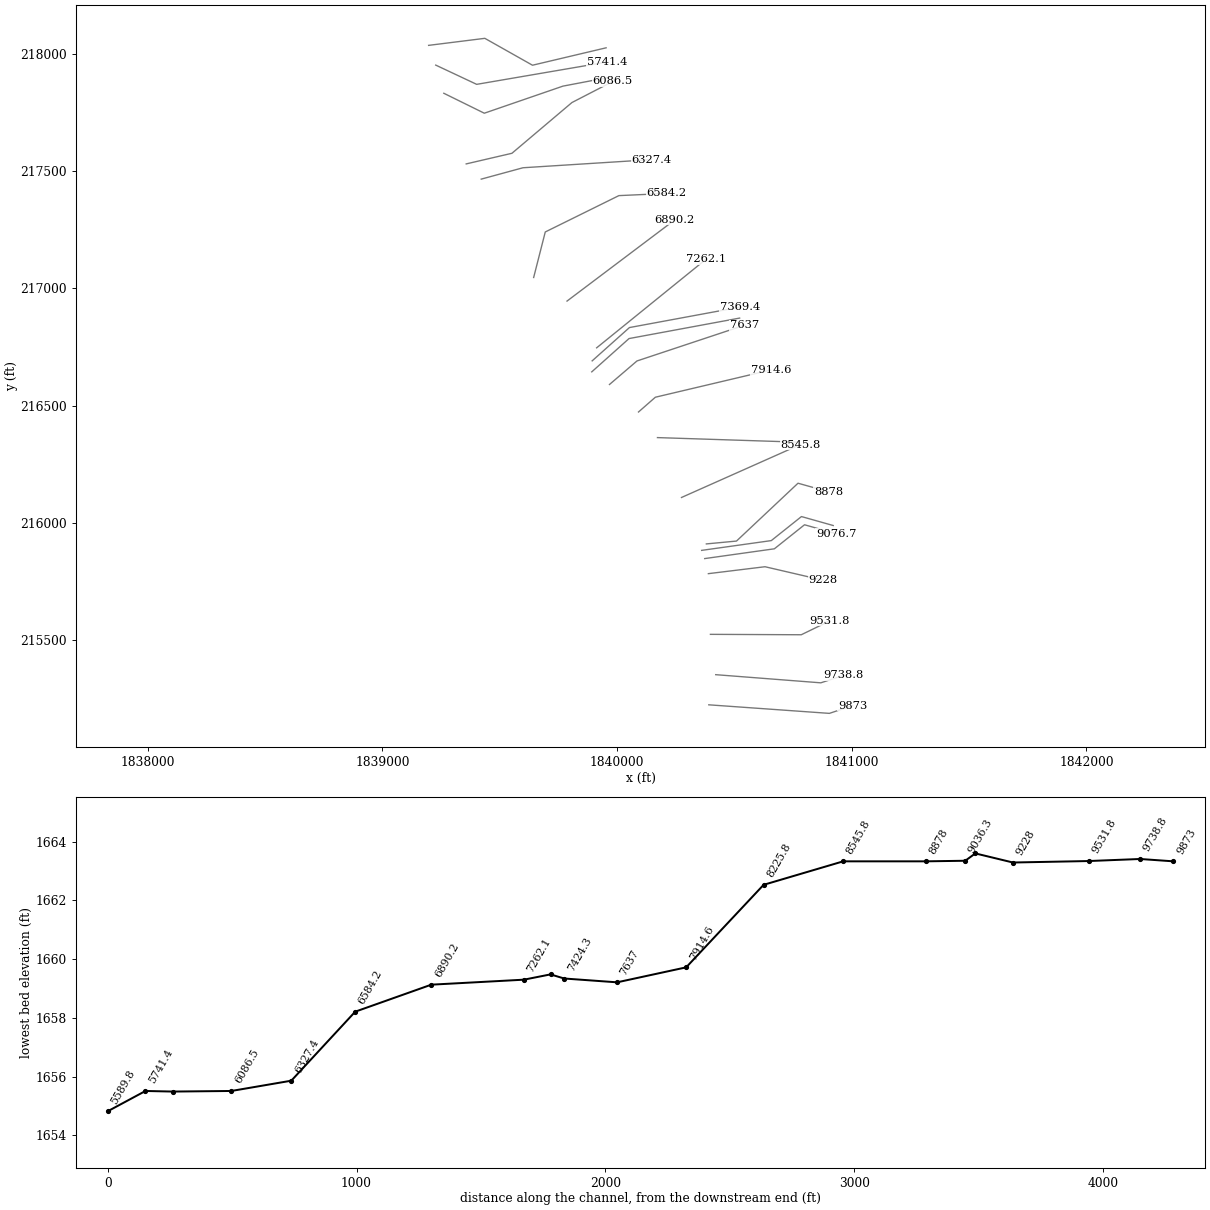
HEC-RAS study BILLSCK.prj: BILLSCK

--- BILLSCK.g01 (geometry) --- (continued)

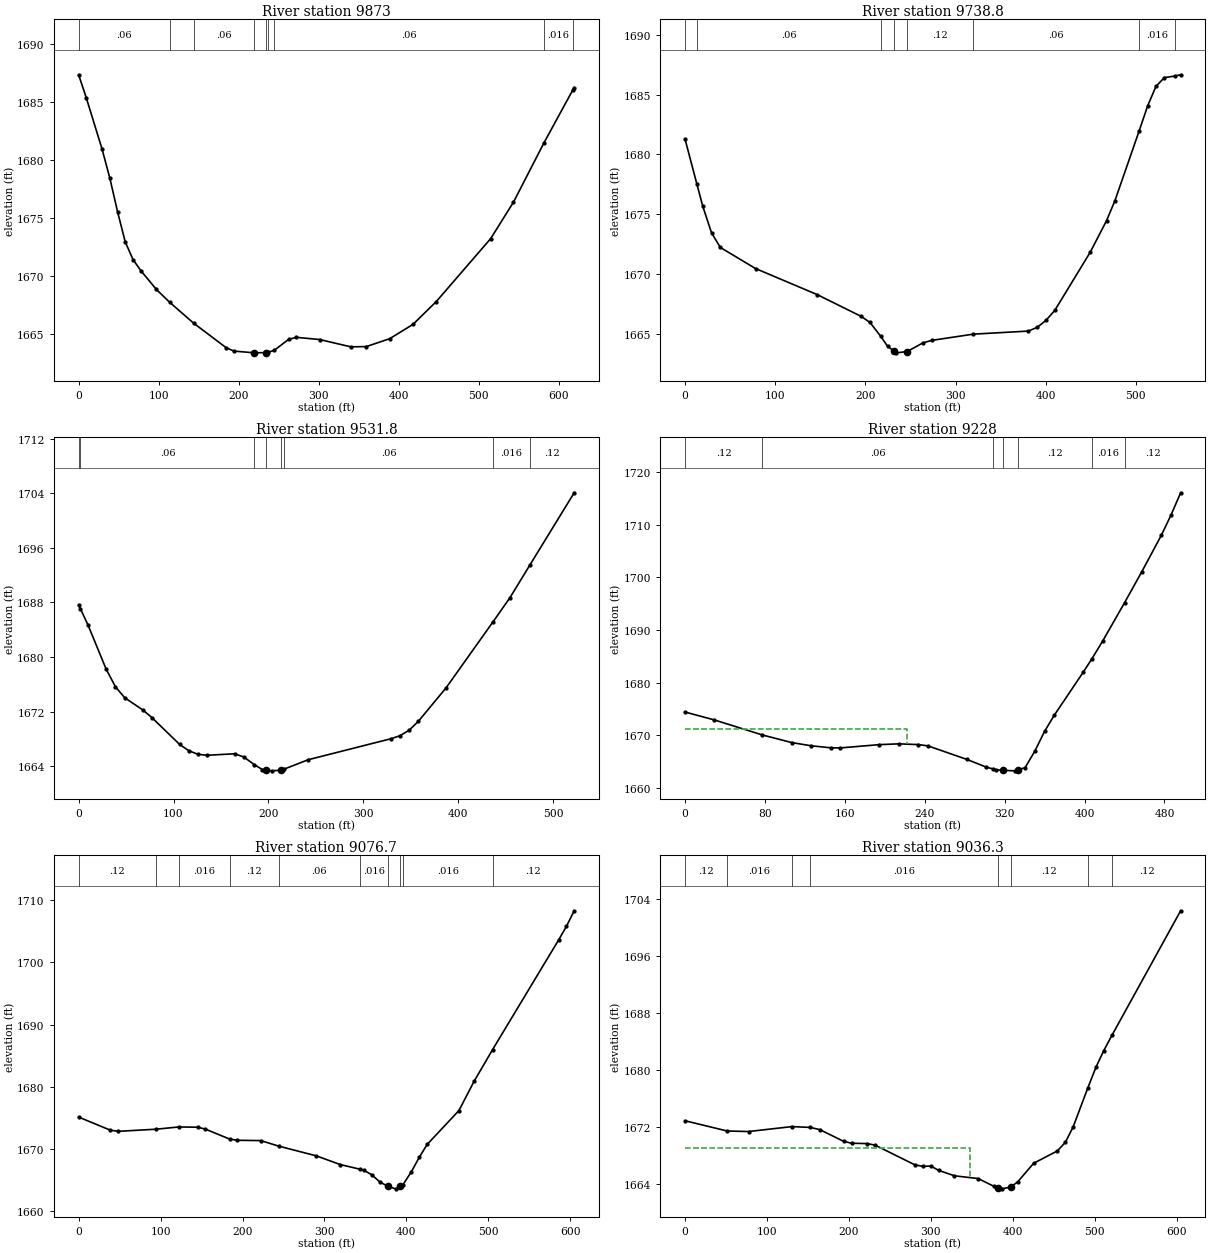
Type RM Length L Ch R = 1 ,9873    ,133.6,134.2,134
XS GIS Cut Line= 3
     1840390.756      215224.886     1840904.645      215188.427
     1841003.603      215221.414
#Sta/Elev= 30
       0 1687.36     9.7 1685.34    29.2 1680.96    38.9 1678.46    48.6 1675.54
    58.3 1672.91      68 1671.39    77.8 1670.43    97.2 1668.81  113.641667.709
  143.611665.903   184.7 1663.76   194.4 1663.48   219.8 1663.33   234.8 1663.35
  236.791663.379  244.531663.546   262.4 1664.49   272.2 1664.67   301.3 1664.48
   340.2 1663.85   359.6 1663.87   388.8 1664.55     418 1665.79   447.1 1667.76
   515.2 1673.21   543.6 1676.35  581.791681.485  617.791686.047   619.5 1686.25
#Mann= 9 ,-1 , 0
       0     .06       0  113.64     .12       0  143.61     .06       0
   219.8    .045       0   234.8     .06       0  236.79     .12       0
  244.53     .06       0  581.79    .016       0  617.79     .12       0
Bank Sta=219.8,234.8
XS Rating Curve= 0 ,0
Exp/Cntr=0.3,0.1

Type RM Length L Ch R = 1 ,9738.8  ,204.9,207,208.4
XS GIS Cut Line= 3
      1840420.27      215353.358     1840868.187      215318.636
     1840963.673      215349.886
#Sta/Elev= 30
       0 1681.26   13.121677.512    19.5 1675.69    29.3 1673.45    39.1 1672.22
    78.1 1670.46   146.5 1668.28   195.3 1666.46   205.1 1665.95  216.851664.807
   224.6 1663.96   231.5 1663.57   234.4 1663.41   246.5 1663.52   263.7 1664.24
   273.5 1664.45  319.551664.972   380.9 1665.23   390.7 1665.55   400.4 1666.13
   410.2 1666.97   449.3 1671.81   467.5 1674.46   476.7 1676.11  503.631681.956
   513.2 1684.08   522.3 1685.68   531.5 1686.42  542.891686.548   549.7 1686.66
#Mann= 8 ,-1 , 0
       0     .12       0   13.12     .06       0  216.85     .12       0
   231.5    .045       0   246.5     .12       0  319.55     .06       0
  503.63    .016       0  542.89     .12       0
Bank Sta=231.5,246.5
XS Rating Curve= 0 ,0
Exp/Cntr=0.3,0.1

Type RM Length L Ch R = 1 ,9531.8  ,308,303.8,298.1
XS GIS Cut Line= 3
     1840397.701      215525.233     1840784.853      215523.497
     1840906.381      215582.525
#Sta/Elev= 30
       0 1687.63    1.951687.053     9.7 1684.76      29 1678.24    38.7 1675.68
    48.4 1674.07    67.8 1672.24    77.4 1671.12   106.5  1667.2   116.2 1666.28
   125.8 1665.76   135.5 1665.62   164.5 1665.84   174.2 1665.36  185.221664.238
   193.6 1663.53  197.341663.457   203.3 1663.34   212.9 1663.42  216.681663.595
     242 1664.97   329.1 1668.04   338.8 1668.49   348.4 1669.29   358.1  1670.6
   387.2 1675.48  436.28 1685.07   454.7 1688.72  475.411693.441   522.3 1704.07
#Mann= 8 ,-1 , 0
       0     .12       0    1.95     .06       0  185.22     .12       0
  197.34    .045       0   212.9     .12       0  216.68     .06       0
  436.28    .016       0  475.41     .12       0
Bank Sta=197.34,212.9
XS Rating Curve= 0 ,0
Exp/Cntr=0.3,0.1

Type RM Length L Ch R = 1 ,9228    ,126,151.3,173
XS GIS Cut Line= 3
      1840389.02      215783.914      1840630.34      215813.427
     1840876.867      215756.136
#Sta/Elev= 30
       0 1674.44    29.2 1672.95   77.371670.096     107 1668.64   126.4 1668.04
   145.9 1667.66   155.6 1667.64   194.5 1668.26   213.9 1668.41   233.4 1668.27
   243.1 1668.03   282.1 1665.46   301.5    1664  308.521663.642   311.3  1663.5
   318.8 1663.38   330.7 1663.29   333.8 1663.49   340.5 1663.91   350.2 1667.03
   359.9 1670.76   369.7 1673.85   398.9 1682.07  407.521684.594   418.3 1687.96
  440.091695.197   457.3 1701.05   476.8 1707.94   486.5 1711.78   496.2 1716.03
#Mann= 7 ,-1 , 0
       0     .12       0   77.37     .06       0  308.52     .12       0
   318.8    .045       0   333.8     .12       0  407.52    .016       0
  440.09     .12       0
#XS Ineff= 2 , 0
          221.88 1671.15
Permanent Ineff=
       F       F
Bank Sta=318.8,333.8
XS Rating Curve= 0 ,0
Exp/Cntr=0.3,0.1

Type RM Length L Ch R = 1 ,9076.7  ,44.9,40.5,39.2
XS GIS Cut Line= 4
     1840373.395       215848.15      1840670.27      215889.816
     1840798.742      215992.247     1840934.159      215954.052
#Sta/Elev= 30
       0 1675.13    38.7 1673.02    48.4 1672.84   94.471673.179  122.321673.542
   145.1  1673.5   154.7  1673.2  184.17  1671.6   193.4  1671.4   222.4 1671.35
  243.961670.469   290.1  1668.9   319.1 1667.51  343.491666.747   348.1 1666.59
   357.8 1665.85   367.4 1664.73   377.5 1663.99   386.8  1663.6   392.5 1664.01
  395.71 1664.24   406.1 1666.34   415.8 1668.68   425.4 1670.74   464.1 1676.17
   482.8 1680.91  505.281685.981     586 1703.62   595.4 1705.78   604.8 1708.27
#Mann= 10 ,-1 , 0
       0     .12       0   94.47     .06       0  122.32    .016       0
  184.17     .12       0  243.96     .06       0  343.49    .016       0
   377.5    .045       0   392.5     .12       0  395.71    .016       0
  505.28     .12       0
Bank Sta=377.5,392.5
XS Rating Curve= 0 ,0
Exp/Cntr=0.3,0.1

Type RM Length L Ch R = 1 ,9036.3  ,148.4,158.3,159
XS GIS Cut Line= 4
     1840360.287      215883.132     1840657.162      215924.799
     1840785.635       216027.23     1840921.051      215989.035
#Sta/Elev= 30
       0  1672.9   51.191671.471    77.4 1671.39  130.491672.085  152.66 1671.97
   164.4 1671.66   193.4 1670.02   203.1 1669.75   222.4  1669.7   232.1 1669.47
   280.4 1666.72   290.1  1666.5   299.8 1666.56   309.4 1665.94   328.8 1665.18
   357.8 1664.79   377.1 1663.69   382.5  1663.5   386.8 1663.35   397.5 1663.61
   406.1 1664.35   425.4 1666.94   454.4 1668.67   464.1 1669.88   473.5 1672.01
  491.511677.513   501.6 1680.46     511 1682.75  521.331684.973   604.8 1702.37
#Mann= 8 ,-1 , 0
       0     .12       0   51.19    .016       0  130.49     .06       0
  152.66    .016       0   382.5    .045       0   397.5     .12       0
  491.51    .016       0  521.33     .12       0
#XS Ineff= 2 , 0
          347.47 1669.12
Permanent Ineff=
       F       F
Bank Sta=382.5,397.5
XS Rating Curve= 0 ,0
Exp/Cntr=0.3,0.1

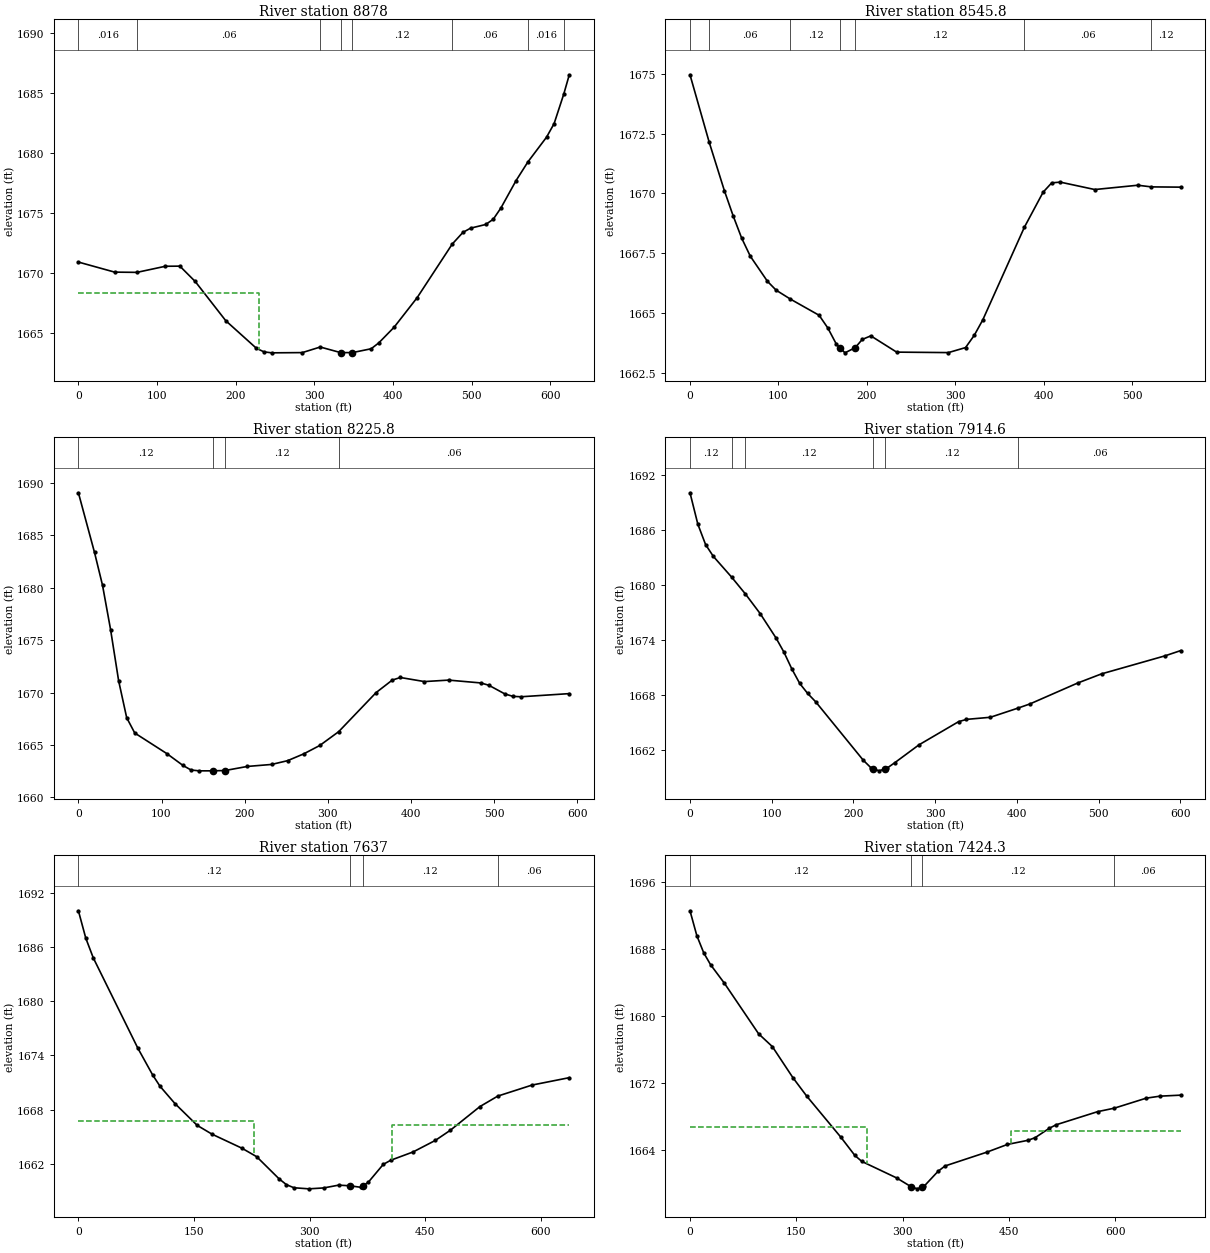
Type RM Length L Ch R = 1 ,8878    ,336.9,332.2,309.6
XS GIS Cut Line= 4
      1840380.34       215910.65     1840508.812      215922.802
     1840770.965       216169.33     1840901.173      216132.872
#Sta/Elev= 30
       0 1670.91    46.1 1670.07   74.47 1670.05   110.6 1670.56     129 1670.57
   148.5 1669.29   187.4 1666.01   226.3 1663.71     236 1663.41   245.8 1663.33
   284.7 1663.35  307.441663.816   333.4 1663.35   348.4 1663.35   372.2 1663.67
   381.9 1664.16   401.4 1665.47   430.6 1667.93  475.271672.411   488.9 1673.39
   498.6 1673.74   517.9 1674.05   527.5 1674.49   537.2 1675.43   556.5 1677.72
  571.551679.279   595.2 1681.34   604.8 1682.47  617.111684.941   624.1 1686.55
#Mann= 8 ,-1 , 0
       0    .016       0   74.47     .06       0  307.44     .12       0
   333.4    .045       0   348.4     .12       0  475.27     .06       0
  571.55    .016       0  617.11     .12       0
#XS Ineff= 2 , 0
          229.72 1668.36
Permanent Ineff=
       F       F
Bank Sta=333.4,348.4
XS Rating Curve= 0 ,0
Exp/Cntr=0.3,0.1

Type RM Length L Ch R = 1 ,8545.8  ,298.3,320,312.4
XS GIS Cut Line= 2
     1840274.437      216108.566     1840781.381      216334.261
#Sta/Elev= 30
       0 1674.96   21.691672.141    38.9 1670.11    48.7 1669.07    58.4 1668.13
    68.2 1667.37    87.6 1666.32    97.4 1665.95  113.581665.576     146  1664.9
   155.8 1664.37   165.5 1663.69  170.111663.519   175.2 1663.33  186.781663.547
   194.7 1663.89   204.4 1664.04   233.6 1663.36   292.1 1663.34   311.5 1663.55
   321.3 1664.06     331 1664.71   378.11668.591   399.2 1670.05   408.9 1670.44
   418.6 1670.47   457.6 1670.16   506.2 1670.34  521.571670.271   554.9 1670.26
#Mann= 7 ,-1 , 0
       0     .12       0   21.69     .06       0  113.58     .12       0
  170.11    .045       0  186.78     .12       0   378.1     .06       0
  521.57     .12       0
Bank Sta=170.11,186.78
XS Rating Curve= 0 ,0
Exp/Cntr=0.3,0.1

Type RM Length L Ch R = 1 ,8225.8  ,301.9,311.2,317.1
XS GIS Cut Line= 2
     1840172.006      216363.775     1840762.284      216344.677
#Sta/Elev= 30
       0 1689.07    19.4 1683.37      29 1680.25    38.7 1676.02    48.4 1671.13
    58.1  1667.6    67.8 1666.14   106.5 1664.17   125.9 1663.04   135.5 1662.61
   145.2 1662.53   161.4 1662.53   176.4 1662.56   203.3 1662.95   232.4 1663.14
   251.7  1663.5   271.1 1664.15   290.4 1664.95  313.141666.268   358.2    1670
   377.6 1671.19   387.3 1671.44   416.3 1671.05   445.4 1671.19   484.1 1670.92
   493.8  1670.7   513.1 1669.87   522.8 1669.64   532.5  1669.6   590.6  1669.9
#Mann= 4 ,-1 , 0
       0     .12       0   161.4    .045       0   176.4     .12       0
  313.14     .06       0
Bank Sta=161.4,176.4
XS Rating Curve= 0 ,0
Exp/Cntr=0.3,0.1

Type RM Length L Ch R = 1 ,7914.6  ,267.8,277.6,275.9
XS GIS Cut Line= 3
     1840091.205      216472.933     1840163.034      216535.828
     1840654.645      216651.969
#Sta/Elev= 30
       0 1690.09     9.6 1686.66    19.1 1684.43    28.6 1683.14   50.81 1680.89
   67.731679.046    85.9 1676.89   105.2 1674.24   114.9 1672.69   124.6 1670.85
   134.3 1669.26     144 1668.17   153.8 1667.26     212 1660.88   221.8 1660.02
   223.8 1659.96   231.5 1659.72   238.8 1659.95   241.2 1660.02   250.9 1660.63
     280 1662.55   328.6 1665.09   338.3 1665.34   367.5 1665.57  401.241666.569
     416 1667.03   474.3 1669.31   503.5 1670.31   581.2 1672.28   600.6 1672.86
#Mann= 6 ,-1 , 0
       0     .12       0   50.81     .08       0   67.73     .12       0
   223.8    .045       0   238.8     .12       0  401.24     .06       0
Bank Sta=223.8,238.8
XS Rating Curve= 0 ,0
Exp/Cntr=0.3,0.1

Type RM Length L Ch R = 1 ,7637    ,199,212.7,172.3
XS GIS Cut Line= 3
     1839967.507       216590.12     1840084.694      216690.381
     1840543.028      216842.724
#Sta/Elev= 30
       0 1690.05     9.6 1687.01    19.3 1684.83    77.1 1674.82    96.4 1671.84
     106 1670.58   125.3 1668.67   154.2 1666.25   173.5 1665.27   212.2 1663.72
   231.5 1662.77   260.5 1660.32   270.1 1659.67   279.8 1659.33   299.1 1659.21
   318.4 1659.31   337.8 1659.62  352.181659.551   366.7 1659.38  369.56 1659.55
   376.4 1659.95   395.7 1661.92   405.4 1662.38   434.4  1663.3   463.3 1664.58
   482.7  1665.7   521.3 1668.34  544.371669.496   588.9 1670.72   637.2 1671.54
#Mann= 4 ,-1 , 0
       0     .12       0  352.18    .045       0  369.56     .12       0
  544.37     .06       0
#XS Ineff= 2 , 0
          228.28 1666.76  407.43         1666.28
Permanent Ineff=
       F       F
Bank Sta=352.18,369.56
XS Rating Curve= 0 ,0
Exp/Cntr=0.3,0.1

Type RM Length L Ch R = 1 ,7424.3  ,66.4,54.9,55.1
XS GIS Cut Line= 3
     1839891.986       216643.94      1840050.84      216785.867
     1840522.194      216873.106
#Sta/Elev= 30
       0 1692.52     9.7 1689.54    19.4  1687.5      29 1686.09    48.4 1683.89
    96.8 1677.84   116.2 1676.31   145.2  1672.6   164.6 1670.41     213 1665.48
   232.6 1663.32   242.4 1662.61   291.3 1660.65   311.7  1659.6   320.6 1659.34
   326.7 1659.55   330.4 1659.67     350 1661.44   359.8 1662.07   418.5 1663.71
   447.8 1664.64   477.2 1665.14   486.9 1665.45   506.5 1666.55   516.3 1666.98
     575 1668.55  598.631668.969   643.5 1670.16     663  1670.4   692.4 1670.52
#Mann= 4 ,-1 , 0
       0     .12       0   311.7    .045       0   326.7     .12       0
  598.63     .06       0
#XS Ineff= 2 , 0
          249.95 1666.76  452.22         1666.28
Permanent Ineff=
       F       F
Bank Sta=311.7,326.7
XS Rating Curve= 0 ,0
Exp/Cntr=0.3,0.1

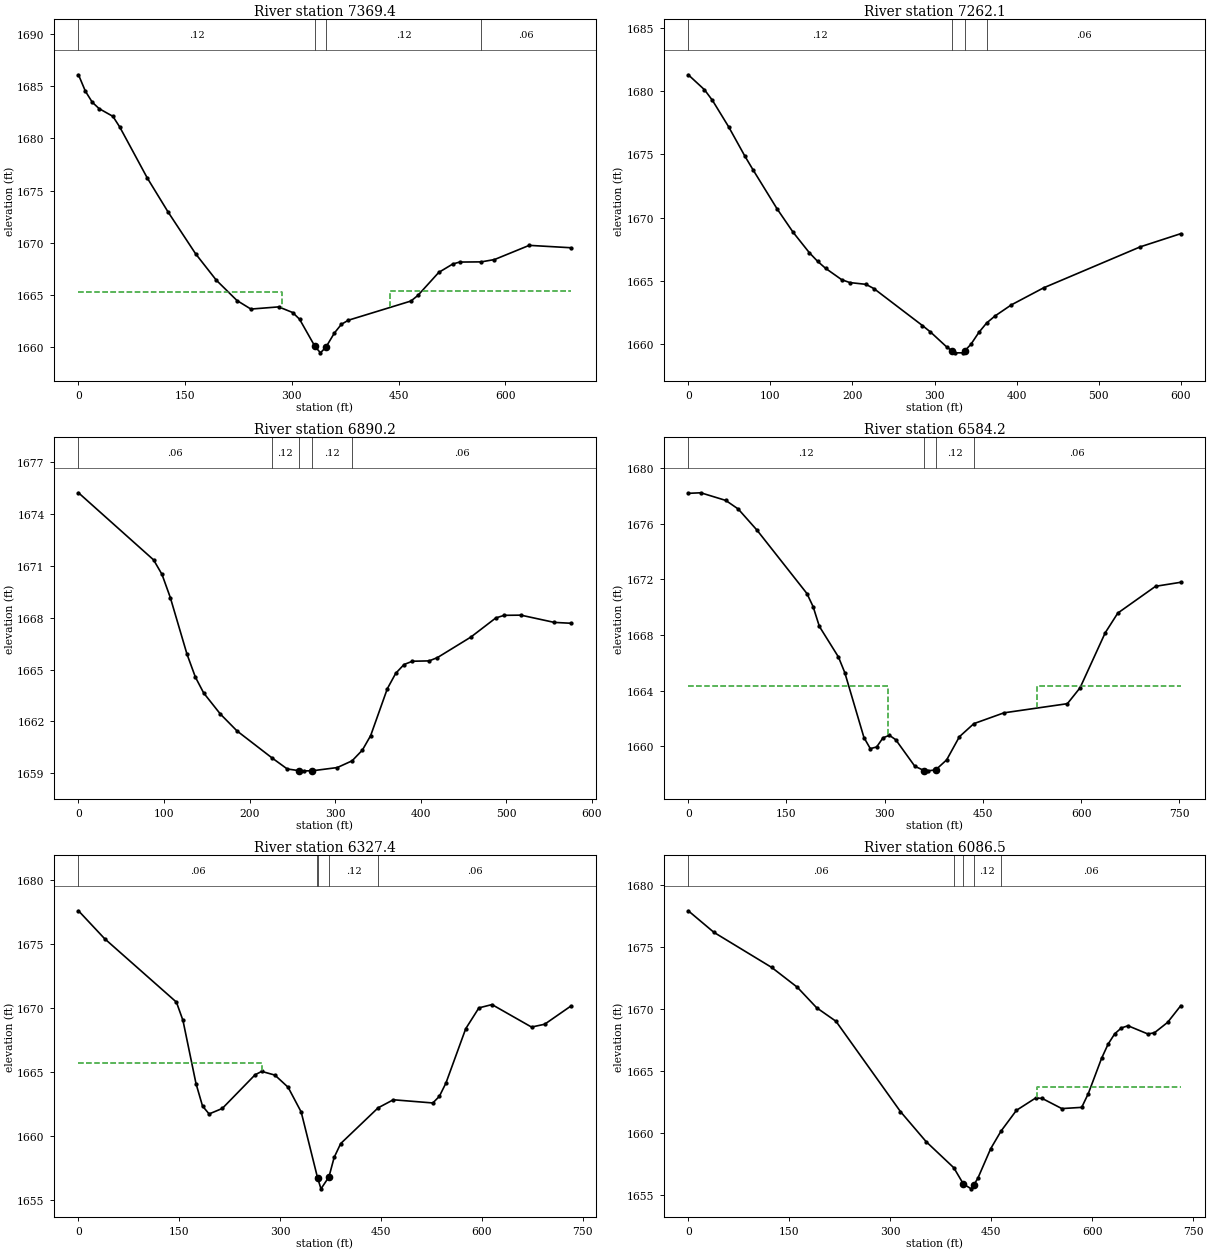
Type RM Length L Ch R = 1 ,7369.4  ,98.3,107.2,115.8
XS GIS Cut Line= 3
     1839893.722      216690.815     1840052.576      216832.742
      1840523.93      216919.981
#Sta/Elev= 30
       0  1686.1     9.7 1684.53    19.4 1683.47      29 1682.86    48.4 1682.12
    58.1 1681.09    96.8 1676.21   125.9 1672.97   164.6 1668.97   193.7 1666.44
   222.8 1664.49   242.4 1663.67   281.5 1663.88   301.1 1663.34   310.8  1662.7
  332.481660.089   340.2 1659.48  347.981660.036   359.8 1661.38   369.6 1662.21
   379.3  1662.6   467.4 1664.44   477.2 1664.98   506.5 1667.18   526.1 1667.98
   535.8 1668.17  566.311668.189   584.8 1668.41   633.7 1669.77   692.4 1669.54
#Mann= 4 ,-1 , 0
       0     .12       0  332.48    .045       0  347.98     .12       0
  566.31     .06       0
#XS Ineff= 2 , 0
          286.07 1665.35  438.49         1665.41
Permanent Ineff=
       F       F
Bank Sta=332.48,347.98
XS Rating Curve= 0 ,0
Exp/Cntr=0.3,0.1

Type RM Length L Ch R = 1 ,7262.1  ,345.7,371.9,322.2
XS GIS Cut Line= 2
     1839912.819       216746.37     1840378.965      217123.974
#Sta/Elev= 30
       0  1681.3    19.7 1680.12    29.5 1679.27    49.2 1677.18    68.8 1674.88
    78.7  1673.8   108.2 1670.69   127.8 1668.83   147.5 1667.22   157.4 1666.55
   167.2 1665.99   186.8 1665.09   196.7 1664.86   216.4 1664.72   226.2 1664.38
   285.2 1661.46     295 1660.95   314.7 1659.77   321.8 1659.43   324.5  1659.3
   334.4  1659.3   336.8 1659.46   344.2 1659.97     354 1660.92  363.471661.666
   373.7 1662.22   393.4 1663.09   432.7 1664.44   550.7 1667.69   599.9 1668.73
#Mann= 4 ,-1 , 0
       0     .12       0   321.8    .045       0   336.8     .12       0
  363.47     .06       0
Bank Sta=321.8,336.8
XS Rating Curve= 0 ,0
Exp/Cntr=0.3,0.1

Type RM Length L Ch R = 1 ,6890.2  ,322,306,298.7
XS GIS Cut Line= 2
     1839786.517      216945.589     1840246.153      217291.943
#Sta/Elev= 30
       0 1675.24    87.8 1671.35    97.6 1670.51   107.3 1669.17   126.8 1665.89
   136.6 1664.56   146.3 1663.64   165.8 1662.42   185.3 1661.44  225.931659.887
   243.9 1659.24   257.7 1659.14   263.4 1659.13   272.7 1659.13   302.4 1659.32
  319.681659.709   331.7 1660.33   341.4 1661.17   360.9 1663.89   370.7 1664.78
   380.4 1665.29   390.2 1665.48   409.7  1665.5   419.4 1665.69   458.5 1666.88
   487.7 1667.99   497.5 1668.14     517 1668.15     556 1667.73   575.5 1667.68
#Mann= 5 ,-1 , 0
       0     .06       0  225.93     .12       0   257.7    .045       0
   272.7     .12       0  319.68     .06       0
Bank Sta=257.7,272.7
XS Rating Curve= 0 ,0
Exp/Cntr=0.3,0.1

Type RM Length L Ch R = 1 ,6584.2  ,250.4,256.8,248.6
XS GIS Cut Line= 4
      1839644.33       217046.11     1839693.809       217240.12
     1840007.611      217395.068     1840209.434      217404.183
#Sta/Elev= 30
       0 1678.21    19.1 1678.25    57.2  1677.7    76.3 1677.08   104.9 1675.56
   181.2 1670.99   190.7 1670.04   200.2 1668.62   229.4 1666.41   239.1 1665.28
   268.3 1660.61     278 1659.81   287.7 1659.93   297.4 1660.59   307.2 1660.77
   316.9 1660.45     346 1658.54   360.6 1658.22   365.5 1658.21  377.751658.275
   394.6    1659   414.1 1660.67  436.181661.612   482.1 1662.39     579 1663.05
   598.3 1664.19   636.8 1668.16     656 1669.58   713.7 1671.51   752.2  1671.8
#Mann= 4 ,-1 , 0
       0     .12       0   360.6    .045       0  377.75     .12       0
  436.18     .06       0
#XS Ineff= 2 , 0
          304.64 1664.33  533.33         1664.29
Permanent Ineff=
       F       F
Bank Sta=360.6,377.75
XS Rating Curve= 0 ,0
Exp/Cntr=0.3,0.1

Type RM Length L Ch R = 1 ,6327.4  ,224.7,240.9,254.5
XS GIS Cut Line= 3
     1839420.892      217465.345     1839598.933      217513.825
     1840145.892      217548.454
#Sta/Elev= 30
       0 1677.62    38.8 1675.44   145.7 1670.47   155.4 1669.04   174.8  1664.1
   184.5 1662.34   194.3 1661.72   213.9 1662.15   262.8 1664.79   272.6 1665.05
   292.2 1664.76   311.8 1663.81   331.3 1661.87  355.351656.779  355.671656.724
   360.7 1655.86  372.551656.794   380.3 1658.32     390  1659.4  445.661662.198
   468.3 1662.83   527.1 1662.58   536.8  1663.1   546.6 1664.14     576 1668.39
   595.6 1670.02   615.1 1670.28   673.9 1668.52   693.4 1668.74   732.6 1670.17
#Mann= 5 ,-1 , 0
       0     .06       0  355.35     .12       0  355.67    .045       0
  372.55     .12       0  445.66     .06       0
#XS Ineff= 2 , 0
          272.45 1665.73
Permanent Ineff=
       F       F
Bank Sta=355.67,372.55
XS Rating Curve= 0 ,0
Exp/Cntr=0.3,0.1

Type RM Length L Ch R = 1 ,6086.5  ,242.8,235.4,226.2
XS GIS Cut Line= 4
      1839356.83      217530.224     1839551.785      217575.489
     1839807.445      217791.734      1839981.83      217881.787
#Sta/Elev= 30
       0 1677.93    38.1 1676.19   123.9 1673.36     162 1671.76   190.6 1670.11
   219.3 1669.02     315 1661.74   353.2 1659.31  394.22 1657.21  408.521655.892
   420.2 1655.51  423.65 1655.81   429.8 1656.35   448.9 1658.74  464.37 1660.17
   487.2 1661.84   515.9 1662.84   525.4  1662.8   554.6 1661.98   584.1 1662.08
   593.9 1663.19   613.5 1666.02   623.3 1667.18   633.1 1668.01   642.9 1668.48
   652.8 1668.66   682.2    1668     692 1668.09   711.6 1668.93   731.2 1670.28
#Mann= 5 ,-1 , 0
       0     .06       0  394.22     .12       0  408.52    .045       0
  423.65     .12       0  464.37     .06       0
#XS Ineff= 2 , 0
                          517.65         1663.74
Permanent Ineff=
       F       F
Bank Sta=408.52,423.65
XS Rating Curve= 0 ,0
Exp/Cntr=0.3,0.1

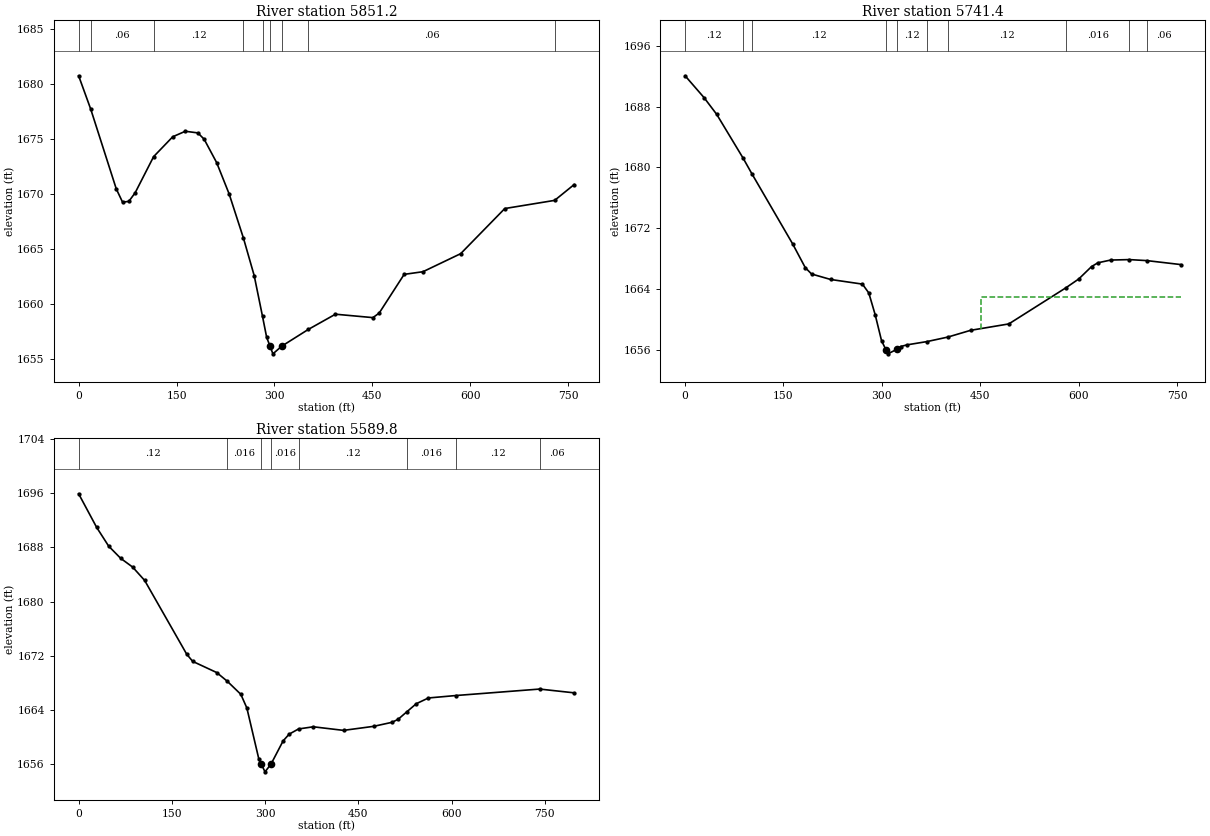
Type RM Length L Ch R = 1 ,5851.2  ,113.4,109.8,106.1
XS GIS Cut Line= 4
     1839261.459      217831.257     1839434.001      217746.288
     1839769.084      217861.664     1839977.881       217901.45
#Sta/Elev= 30
       0 1680.75   18.53 1677.72    57.7 1670.47    67.3 1669.27    76.9 1669.34
    86.6 1670.12  114.921673.406   144.2 1675.21   163.5 1675.71   182.7 1675.56
   192.3 1674.99   211.5 1672.86   230.6 1670.02  252.481666.014     269  1662.6
  281.761658.892   288.1 1656.99  293.17  1656.2   297.7 1655.49  311.161656.184
  351.971657.709   393.5 1659.09   450.9 1658.78   460.5 1659.19   498.8 1662.71
   527.6 1662.95   585.4 1664.59     653 1668.69  729.371669.431   759.3 1670.87
#Mann= 9 ,-1 , 0
       0     .12       0   18.53     .06       0  114.92     .12       0
  252.48     .06       0  281.76     .12       0  293.17    .045       0
  311.16     .12       0  351.97     .06       0  729.37    .016       0
Bank Sta=293.17,311.16
XS Rating Curve= 0 ,0
Exp/Cntr=0.3,0.1

Type RM Length L Ch R = 1 ,5741.4  ,168.8,151.6,133.8
XS GIS Cut Line= 3
     1839226.969      217951.318     1839401.448      217869.287
     1839956.135      217964.339
#Sta/Elev= 30
       0 1692.04    28.9 1689.17    48.2 1686.97   88.38 1681.23  101.62  1679.2
   163.9 1669.97   183.2 1666.84   192.8    1666   221.9 1665.28   270.4 1664.67
   280.1 1663.51   289.8 1660.66   299.5 1657.25  306.08 1656.07   309.2 1655.51
  322.881656.104   328.6 1656.47   338.4 1656.69     3691657.124  400.611657.713
   435.4  1658.6   493.6 1659.44  580.671664.188   600.3 1665.35   619.7 1666.97
   629.4 1667.47   648.8 1667.83  677.371667.891  704.221667.757   755.6 1667.24
#Mann= 10 ,-1 , 0
       0     .12       0   88.38     .06       0  101.62     .12       0
  306.08    .045       0  322.88     .12       0     369     .06       0
  400.61     .12       0  580.67    .016       0  677.37     .12       0
  704.22     .06       0
#XS Ineff= 2 , 0
                          450.77         1662.97
Permanent Ineff=
       F       F
Bank Sta=306.08,322.88
XS Rating Curve= 0 ,0
Exp/Cntr=0.3,0.1

Type RM Length L Ch R = 1 ,5589.8  ,54,55,56.4
XS GIS Cut Line= 4
     1839196.673      218035.433     1839436.257      218065.381
     1839639.382      217950.797     1839953.184      218025.016
#Sta/Elev= 30
       0 1695.93      29 1690.96    48.3 1688.19    67.6 1686.39    86.9 1685.09
   106.2 1683.12   173.8 1672.22   183.5 1671.15   222.1  1669.5  238.981668.224
   260.9 1666.28   270.6 1664.26     290 1656.66  293.781655.952   299.8 1654.82
   309.5 1655.97   328.9 1659.39   338.6 1660.39  353.781661.162   377.5 1661.48
   426.1 1660.95   474.7 1661.55     504 1662.14   513.8 1662.58  528.361663.732
   543.1 1664.89   562.6 1665.74  606.53  1666.1   741.51667.058   797.1  1666.5
#Mann= 8 ,-1 , 0
       0     .12       0  238.98    .016       0  293.78    .045       0
   309.5    .016       0  353.78     .12       0  528.36    .016       0
  606.53     .12       0   741.5     .06       0
Bank Sta=293.78,309.5
XS Rating Curve= 0 ,0
Exp/Cntr=0.3,0.1