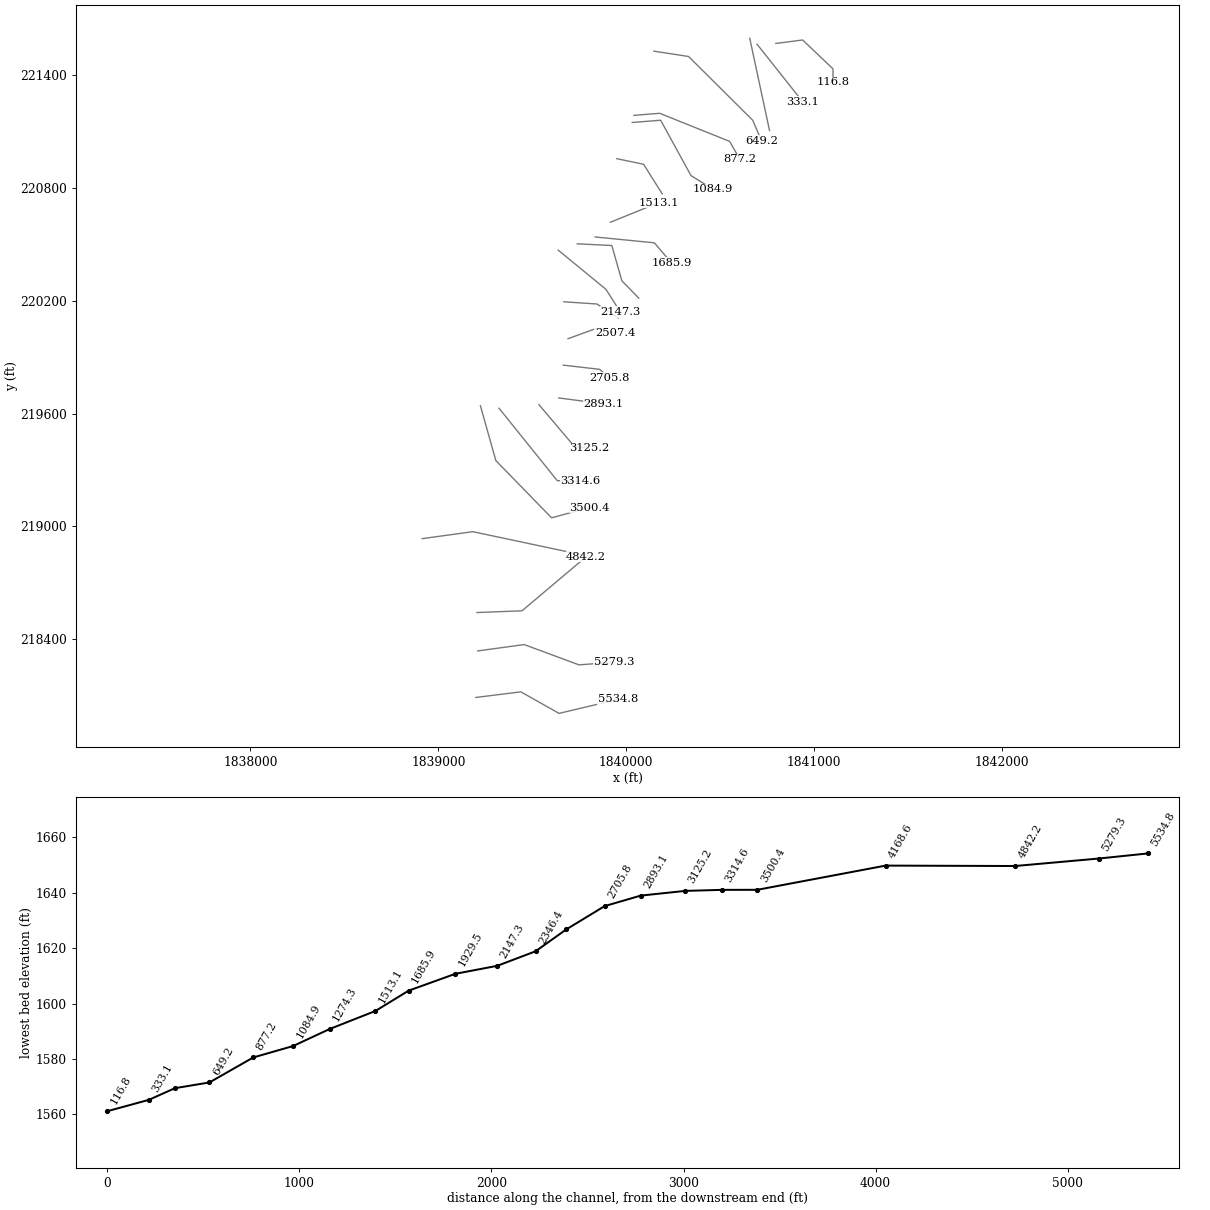
HEC-RAS study BILLSCK.prj: BILLSCK

--- BILLSCK.g01 (geometry) --- (continued)

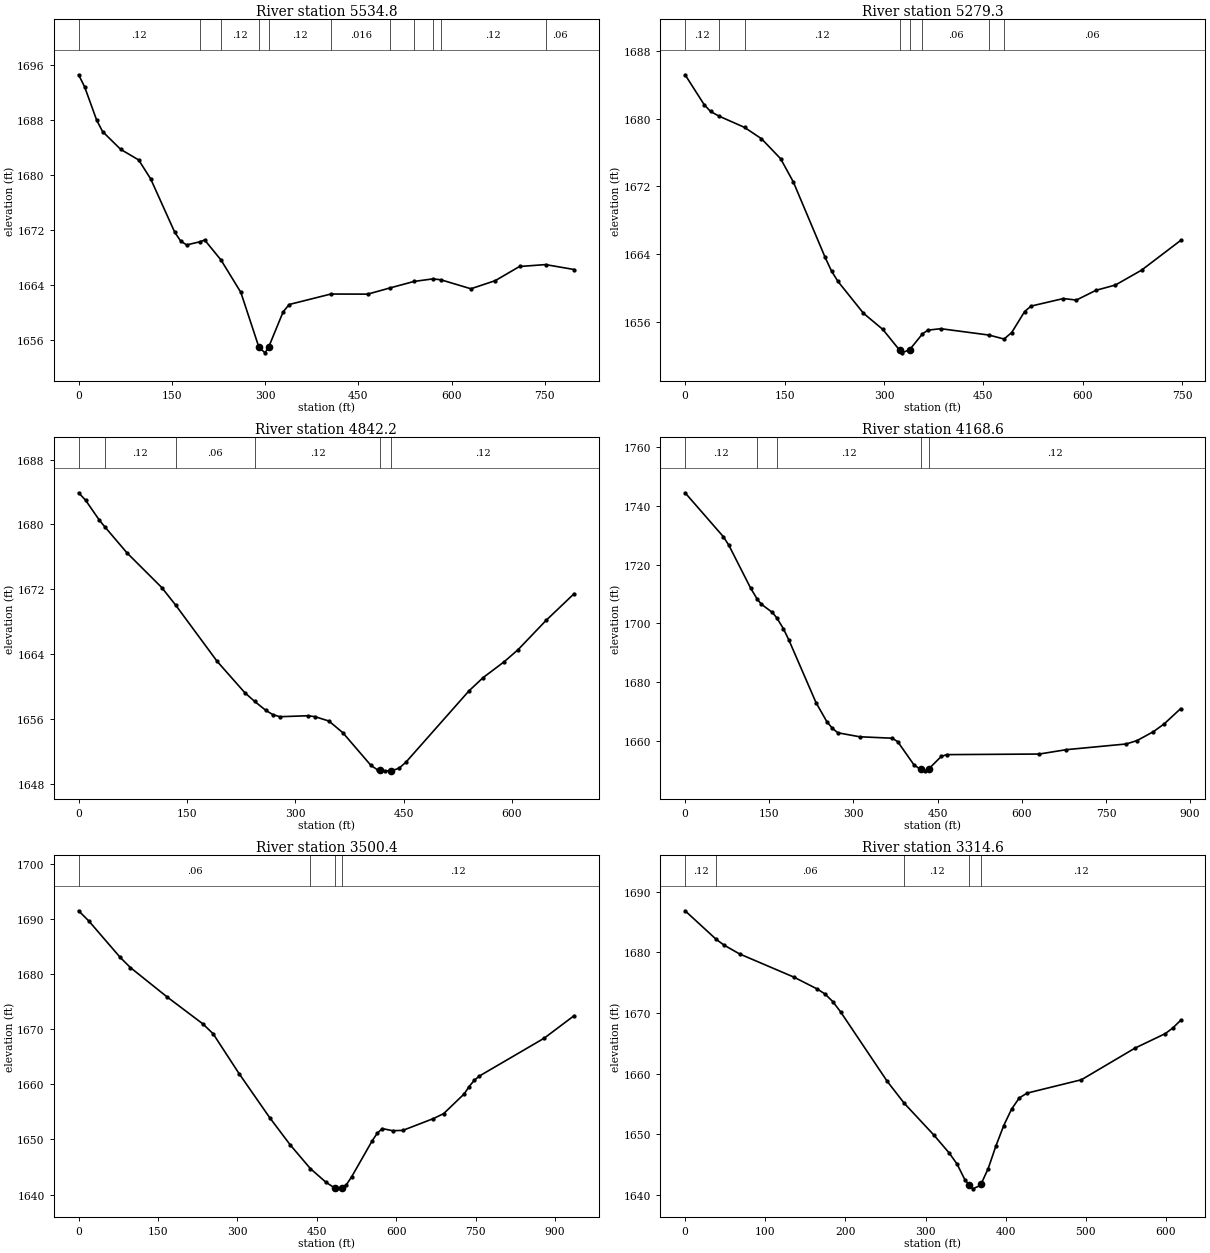
Type RM Length L Ch R = 1 ,5534.8  ,250.9,255.5,259.9
XS GIS Cut Line= 4
     1839199.278      218088.818     1839438.861      218118.766
     1839641.986      218004.183     1839955.788      218078.401
#Sta/Elev= 30
       0 1694.63     9.7 1692.86      29 1688.03    38.6 1686.36    67.6 1683.78
    96.6 1682.24   115.9 1679.48   154.5 1671.74   164.2 1670.43   173.8 1669.88
  194.651670.327   202.8 1670.59  229.121667.672   260.9 1662.98     290 1654.99
   299.8 1654.18  305.451654.968   328.9 1660.13   338.6 1661.21  405.731662.735
     465 1662.72  501.521663.637  539.541664.566  570.011664.942  582.851664.802
     631  1663.5   670.1 1664.68   709.2 1666.74   751.11667.017   797.1  1666.3
#Mann= 11 ,-1 , 0
       0     .12       0  194.65    .016       0  229.12     .12       0
     290    .045       0  305.45     .12       0  405.73    .016       0
  501.52     .06       0  539.54     .12       0  570.01     .06       0
  582.85     .12       0   751.1     .06       0
Bank Sta=290,305.45
XS Rating Curve= 0 ,0
Exp/Cntr=0.3,0.1

Type RM Length L Ch R = 1 ,5279.3  ,387.3,437.1,462.4
XS GIS Cut Line= 4
     1839209.434      218336.474      1839456.83      218370.329
     1839748.496      218262.256     1839934.694      218276.579
#Sta/Elev= 30
       0 1685.17    28.8 1681.64    38.4 1680.84   51.041680.293   89.61 1678.96
   115.2 1677.62   144.1 1675.26   163.3 1672.51   211.3  1663.6   220.9 1661.99
   230.5 1660.78   269.1 1657.01   298.3  1655.1  323.651652.648   327.5 1652.34
  338.931652.734  358.081654.579   366.3 1655.02   385.8 1655.19  458.591654.437
  481.12 1653.97   492.7 1654.74   512.2 1657.22   521.9 1657.86   570.6 1658.75
   590.2 1658.57   619.7 1659.72   649.2 1660.35   688.5  1662.1   747.5 1665.61
#Mann= 8 ,-1 , 0
       0     .12       0   51.04    .016       0   89.61     .12       0
  323.65    .045       0  338.93     .12       0  358.08     .06       0
  458.59     .12       0  481.12     .06       0
Bank Sta=323.65,338.93
XS Rating Curve= 0 ,0
Exp/Cntr=0.3,0.1

Type RM Length L Ch R = 1 ,4842.2  ,691.8,673.6,651.7
XS GIS Cut Line= 3
     1839205.528      218540.901     1839445.111      218550.016
     1839786.257      218837.776
#Sta/Elev= 30
       0  1683.9     9.6 1682.99    28.8 1680.51   36.031679.727    67.1 1676.48
   115.1 1672.22  134.341670.055   191.8 1663.12   230.2 1659.25  243.611658.195
   259.2 1657.08   268.9 1656.56   278.6  1656.3   317.4 1656.42   327.1 1656.31
   346.5 1655.77   365.9 1654.32   404.7  1650.3   414.4 1649.72   417.8 1649.69
   424.1 1649.63   432.8 1649.63   443.5 1649.94   453.2  1650.7   540.5 1659.49
   559.9 1661.11     589 1663.06   608.4 1664.56   647.2 1668.17   686.1 1671.47
#Mann= 6 ,-1 , 0
       0    .016       0   36.03     .12       0  134.34     .06       0
  243.61     .12       0   417.8    .045       0   432.8     .12       0
Bank Sta=417.8,432.8
XS Rating Curve= 0 ,0
Exp/Cntr=0.3,0.1

Type RM Length L Ch R = 1 ,4168.6  ,680,668.2,651.7
XS GIS Cut Line= 3
     1838913.861      218934.131     1839183.568      218971.117
     1839781.048      218844.287
#Sta/Elev= 30
       0 1744.46    68.1 1729.52    77.8 1726.65   116.7 1712.02  128.751708.185
   136.1 1706.48   155.6 1703.71  163.541701.819     175 1698.23   184.7 1694.42
   233.3    1673   252.8 1666.45   262.5 1664.25   272.2 1662.74     311 1661.38
   369.2 1660.89   378.9  1659.7     408 1651.77   419.5 1650.28   427.4 1649.78
   434.5  1650.5   456.4 1654.67   466.1  1655.3     631  1655.5   679.4 1656.99
   786.1 1658.93   805.5  1660.1   834.6 1663.13   853.9  1665.8     883 1670.96
#Mann= 5 ,-1 , 0
       0     .12       0  128.75    .016       0  163.54     .12       0
   419.5    .045       0   434.5     .12       0
Bank Sta=419.5,434.5
XS Rating Curve= 0 ,0
Exp/Cntr=0.3,0.1

Type RM Length L Ch R = 1 ,3500.4  ,187.4,185.8,184.8
XS GIS Cut Line= 4
     1839223.757      219641.162     1839305.788      219349.495
     1839602.663      219044.808     1839803.184      219099.495
#Sta/Elev= 30
       0 1691.48    19.6 1689.59    78.2 1683.06    97.7 1681.19   166.2 1675.92
   234.6 1670.97   254.1 1669.17     303 1661.96     361 1653.95   399.7 1649.02
  437.72 1644.72   467.3 1642.23   483.5 1641.21   486.7 1641.04   498.5 1641.26
     506 1641.81   515.7 1643.21   554.4 1649.72     564 1651.11   573.7 1651.97
     593 1651.59   612.4 1651.64   670.4 1653.79   689.7 1654.69   728.4 1658.26
   737.8  1659.6   747.3 1660.71   756.7 1661.48   879.6 1668.37   936.2 1672.46
#Mann= 4 ,-1 , 0
       0     .06       0  437.72     .12       0   483.5    .045       0
   498.5     .12       0
Bank Sta=483.5,498.5
XS Rating Curve= 0 ,0
Exp/Cntr=0.3,0.1

Type RM Length L Ch R = 1 ,3314.6  ,188.6,189.4,189.6
XS GIS Cut Line= 3
     1839322.715      219628.141     1839632.611      219242.724
     1839756.309      219238.818
#Sta/Elev= 30
       0 1686.86   38.891682.141    48.5 1681.21    67.9 1679.75   135.8 1675.92
   164.8 1673.97   174.6 1673.14   184.2  1671.9   193.9 1670.22   252.1 1658.76
  273.561655.109   310.3  1649.9   329.7  1646.9   339.4 1645.09   349.1 1642.52
  354.431641.699   358.8 1641.02   368.5 1641.58  369.341641.822   378.2 1644.37
   387.9 1648.12   397.6 1651.46   407.3 1654.15     417 1656.01   426.7  1656.8
   494.6 1659.01   561.2 1664.21   599.3 1666.62   608.8 1667.57   618.3  1668.8
#Mann= 5 ,-1 , 0
       0     .12       0   38.89     .06       0  273.56     .12       0
  354.43    .045       0  369.34     .12       0
Bank Sta=354.43,369.34
XS Rating Curve= 0 ,0
Exp/Cntr=0.3,0.1

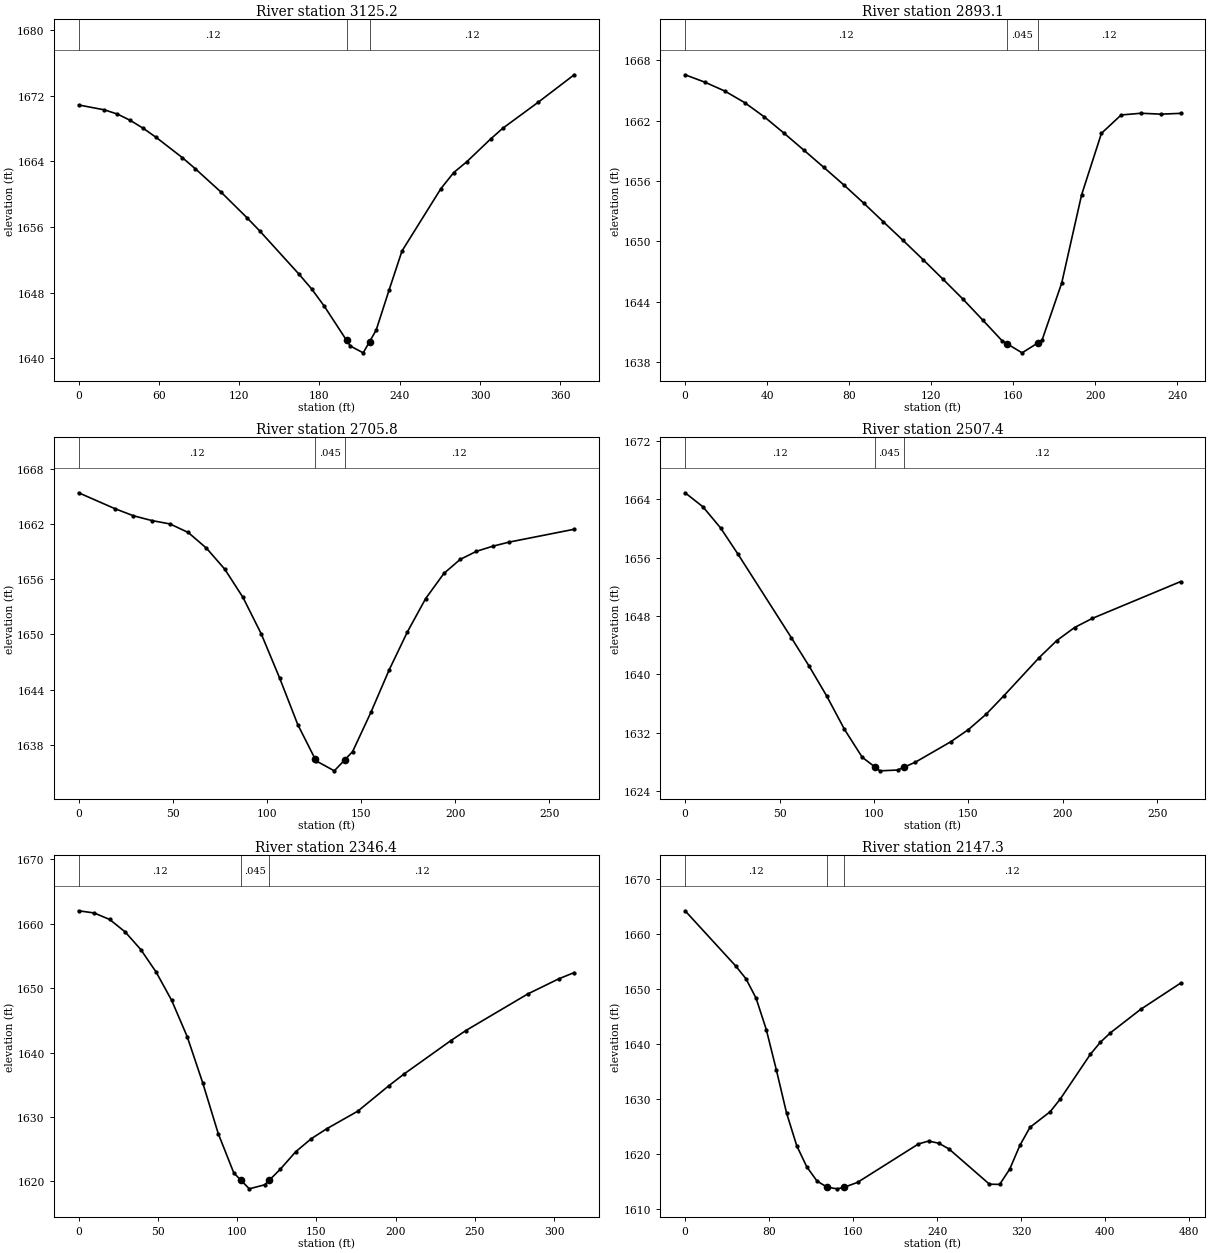
Type RM Length L Ch R = 1 ,3125.2  ,215.2,232.1,248.7
XS GIS Cut Line= 3
     1839534.955      219647.412     1839722.455      219426.058
     1839801.882      219414.339
#Sta/Elev= 28
       0 1670.88    19.3 1670.28      29 1669.77    38.7 1668.99    48.4 1668.02
      58 1666.92    77.4 1664.47      87 1663.13   106.4 1660.26   125.7 1657.15
   135.4 1655.51   164.4  1650.3   174.1 1648.46   183.7 1646.32  200.33 1642.16
   203.1 1641.48   212.7 1640.65  217.451642.009   222.4 1643.42   232.1 1648.33
   241.7 1653.07   270.8 1660.68   280.4 1662.64   290.1 1663.95   307.9 1666.72
   316.9 1668.02   343.6 1671.22   370.4 1674.56
#Mann= 3 ,-1 , 0
       0     .12       0  200.33    .045       0  217.45     .12       0
Bank Sta=200.33,217.45
XS Rating Curve= 0 ,0
Exp/Cntr=0.3,0.1

Type RM Length L Ch R = 1 ,2893.1  ,185.9,187.3,187.4
XS GIS Cut Line= 2
     1839640.423      219682.829     1839880.007      219651.579
#Sta/Elev= 28
       0 1666.55     9.7 1665.81    19.3 1664.94      29 1663.79    38.7 1662.36
    48.3 1660.74      58 1659.05    67.6 1657.36    77.3 1655.63      87 1653.82
    96.6 1651.96   106.3  1650.1     116  1648.2   125.6 1646.28   135.3 1644.31
     145 1642.22   154.6 1640.13   156.9 1639.85   164.3 1638.94   171.9 1639.91
     174 1640.18   183.6 1645.86   193.3 1654.62     203 1660.74   212.6 1662.56
   222.3 1662.73     232 1662.64   241.6 1662.72
#Mann= 3 ,-1 , 0
       0     .12       0   156.9    .045       0   171.9     .12       0
Bank Sta=156.9,171.9
XS Rating Curve= 0 ,0
Exp/Cntr=0.3,0.1

Type RM Length L Ch R = 1 ,2705.8  ,188.4,198.4,208.5
XS GIS Cut Line= 3
     1839665.163      219857.308     1839857.871      219835.172
     1839909.955      219789.599
#Sta/Elev= 27
       0 1665.41    19.4 1663.67    29.1 1662.91    38.8 1662.39    48.5 1662.02
    58.2 1661.09    67.9 1659.38    77.6  1657.1    87.3 1654.02      97 1650.05
   106.7 1645.28   116.4 1640.18  125.721636.394   126.1 1636.24   135.8 1635.15
  141.251636.323   145.5 1637.24   155.2  1641.5   164.9 1646.12   174.6 1650.26
   184.3 1653.89     194 1656.63   202.6 1658.15   211.3 1659.04   219.9 1659.59
   228.6 1660.04   263.2 1661.44
#Mann= 3 ,-1 , 0
       0     .12       0  125.72    .045       0  141.25     .12       0
Bank Sta=125.72,141.25
XS Rating Curve= 0 ,0
Exp/Cntr=0.3,0.1

Type RM Length L Ch R = 1 ,2507.4  ,170.4,160.9,149.8
XS GIS Cut Line= 3
     1839689.903      219997.933     1839839.642       220052.62
     1839939.903      220029.183
#Sta/Elev= 23
       0  1664.9     9.4 1662.99    18.8 1660.08    28.1 1656.45    56.3 1645.02
    65.6 1641.17      75 1637.04    84.4 1632.47    93.8 1628.65  100.461627.332
   103.2 1626.79   112.5  1626.9  115.681627.263   121.9 1627.97   140.7 1630.78
     150 1632.44   159.4 1634.55   168.8 1637.08   187.5 1642.31   196.8 1644.64
   206.2 1646.43   215.6 1647.68   262.4 1652.73
#Mann= 3 ,-1 , 0
       0     .12       0  100.46    .045       0  115.68     .12       0
Bank Sta=100.46,115.68
XS Rating Curve= 0 ,0
Exp/Cntr=0.3,0.1

Type RM Length L Ch R = 1 ,2346.4  ,214.2,199.1,187.1
XS GIS Cut Line= 3
     1839667.767      220194.547     1839843.548      220182.829
     1839958.132       220108.61
#Sta/Elev= 27
       0    1662     9.8 1661.66    19.6 1660.65    29.4 1658.71    39.2 1655.99
    48.9 1652.49    58.7  1648.1    68.5 1642.48    78.3  1635.3    88.1 1627.42
    97.9 1621.33  102.471620.173   107.7 1618.85   117.4 1619.48  120.141620.151
   127.2 1621.88     137 1624.61   146.8 1626.63   156.6 1628.18   176.2 1630.91
   195.7 1634.84   205.4 1636.68   234.7 1641.82   244.4 1643.42   283.4 1649.09
   302.9 1651.43   312.7 1652.41
#Mann= 3 ,-1 , 0
       0     .12       0  102.47    .045       0  120.14     .12       0
Bank Sta=102.47,120.14
XS Rating Curve= 0 ,0
Exp/Cntr=0.3,0.1

Type RM Length L Ch R = 1 ,2147.3  ,231.5,217.9,196.4
XS GIS Cut Line= 3
     1839637.819      220469.287     1839891.726      220260.954
     1839968.548       220139.86
#Sta/Elev= 30
       0 1664.25    48.3 1654.17      58 1651.86    67.6 1648.32    77.3 1642.62
    86.9 1635.25    96.6 1627.42   106.3 1621.46   115.9  1617.6   125.6 1615.03
   135.2 1613.91   144.9 1613.61  151.321613.884   164.2 1614.79   222.2 1621.79
   231.8 1622.31   241.5 1621.92   251.2 1620.88   289.8 1614.45   299.5 1614.42
   309.1 1617.21   318.8 1621.55   328.4 1624.82   347.6 1627.66   357.1 1629.94
   385.8  1638.1   395.4 1640.31   404.9 1642.02   433.6 1646.28   471.8 1651.08
#Mann= 3 ,-1 , 0
       0     .12       0   135.2    .045       0  151.32     .12       0
Bank Sta=135.2,151.32
XS Rating Curve= 0 ,0
Exp/Cntr=0.3,0.1

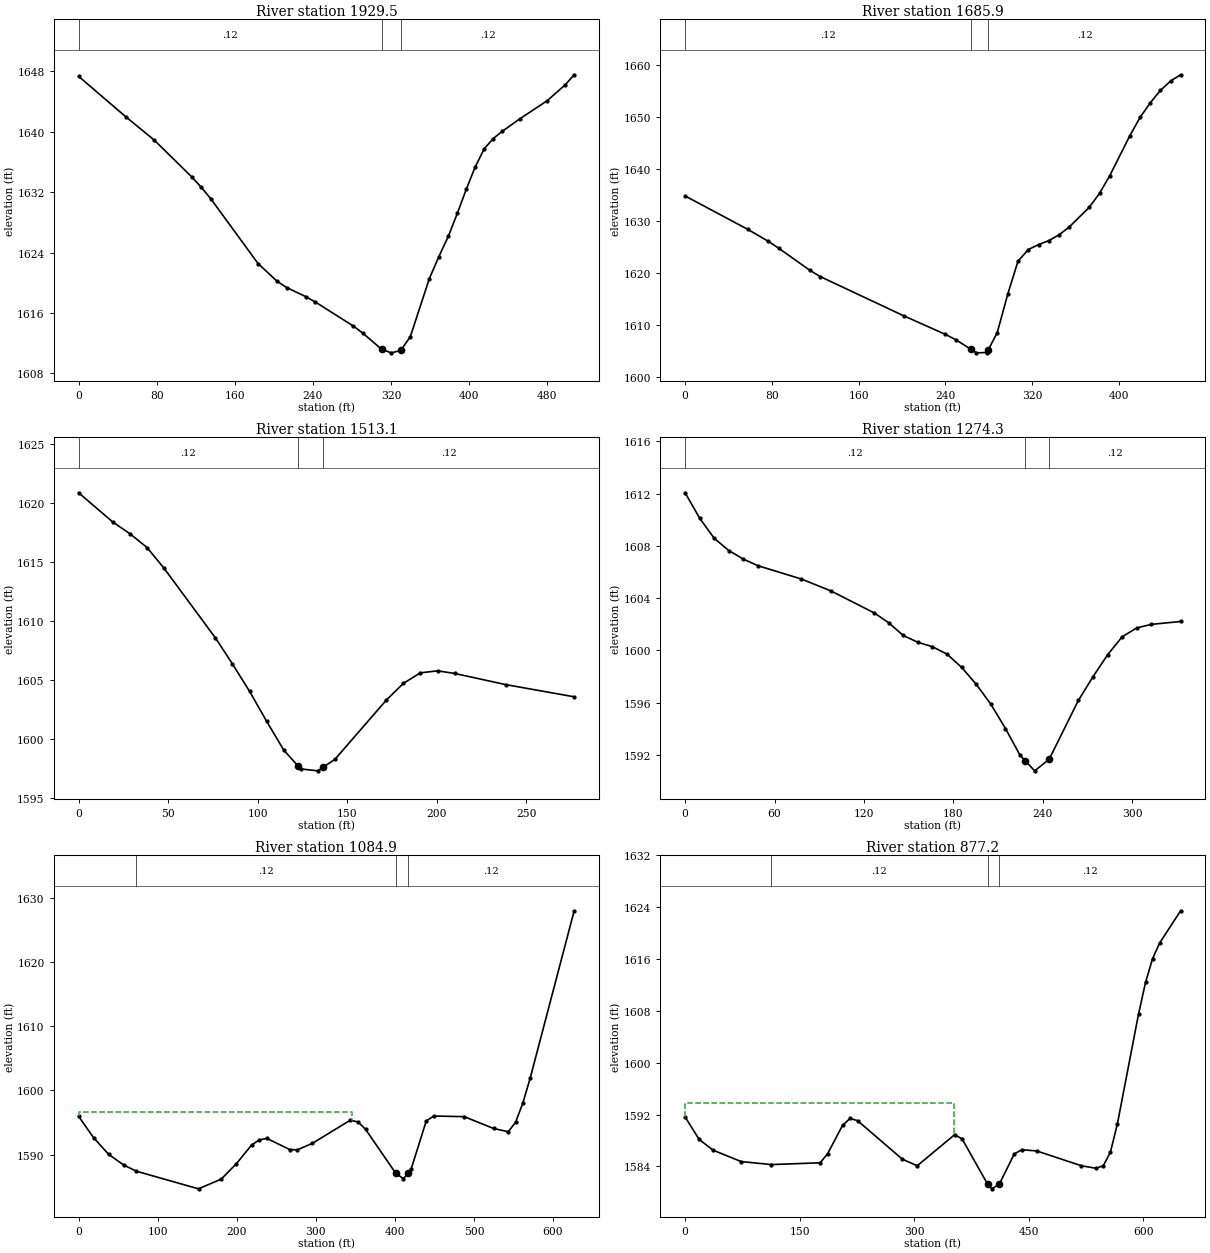
Type RM Length L Ch R = 1 ,1929.5  ,215.5,243.6,270.4
XS GIS Cut Line= 4
     1839739.382      220503.141     1839922.976      220494.026
     1839976.361      220306.526     1840066.205      220214.079
#Sta/Elev= 30
       0 1647.34    48.4 1641.98    77.4 1638.91   116.1    1634   125.8 1632.63
   135.4 1631.13   183.8 1622.56   203.3 1620.21   213.1 1619.38   232.6 1618.18
   242.3 1617.48   281.3 1614.29     291 1613.35   310.5  1611.2   320.3 1610.73
     330 1611.04   339.8 1612.87   359.3 1620.55     369 1623.46   378.8 1626.17
     388 1629.21   397.2  1632.4   406.4 1635.38   415.6 1637.76   424.8 1639.11
     434 1640.06   452.4 1641.75   480.1 1644.12   498.5 1646.22   507.7 1647.55
#Mann= 3 ,-1 , 0
       0     .12       0   310.5    .045       0     330     .12       0
Bank Sta=310.5,330
XS Rating Curve= 0 ,0
Exp/Cntr=0.3,0.1

Type RM Length L Ch R = 1 ,1685.9  ,161.7,172.8,183.7
XS GIS Cut Line= 3
     1839834.434      220539.599     1840149.538      220508.349
     1840240.684      220401.579
#Sta/Elev= 30
       0 1634.84    57.6 1628.43    76.8  1626.1    86.4 1624.77   115.2  1620.5
   124.7 1619.31   201.5 1611.78   239.9 1608.21   249.5 1607.18  263.811605.298
   268.7 1604.64   278.3  1604.7  279.731605.272   287.9 1608.55   297.5  1615.9
     307 1622.28   316.6 1624.53     326 1625.48   335.4 1626.23   344.7 1627.34
   354.1 1628.83   372.8 1632.67   382.2 1635.34   391.5 1638.69   410.2 1646.45
   419.6 1649.95     429 1652.77   438.3 1655.14   447.7 1656.96     457 1658.16
#Mann= 3 ,-1 , 0
       0     .12       0  263.81    .045       0  279.73     .12       0
Bank Sta=263.81,279.73
XS Rating Curve= 0 ,0
Exp/Cntr=0.3,0.1

Type RM Length L Ch R = 1 ,1513.1  ,270.5,238.8,207
XS GIS Cut Line= 2
     1839915.163      220617.724     1840171.673      220721.891
#Sta/Elev= 22
       0 1620.86    19.1 1618.38    28.6  1617.4    38.2 1616.22    47.7 1614.47
    76.4 1608.57    85.9 1606.37    95.5 1604.04     105 1601.51   114.6 1599.06
  122.571597.726   124.1 1597.47   133.6 1597.31  136.481597.603   143.2 1598.29
   171.8 1603.29   181.4 1604.72   190.9 1605.61   200.5 1605.78     210 1605.56
   238.7 1604.61   276.8 1603.58
#Mann= 3 ,-1 , 0
       0     .12       0  122.57    .045       0  136.48     .12       0
Bank Sta=122.57,136.48
XS Rating Curve= 0 ,0
Exp/Cntr=0.3,0.1

Type RM Length L Ch R = 1 ,1274.3  ,190.7,189.4,188
XS GIS Cut Line= 3
     1839949.017      220956.266     1840092.246      220926.318
     1840191.205      220768.766
#Sta/Elev= 29
       0 1612.06     9.8 1610.11    19.5 1608.58    29.3 1607.64      39 1606.99
    48.8 1606.48      78 1605.46    97.6 1604.56   126.8 1602.87   136.6 1602.11
   146.3 1601.14   156.1 1600.62   165.9 1600.28   175.7 1599.71   185.5  1598.7
   195.3  1597.4   205.1 1595.88   214.9 1594.02   224.7 1591.97  228.071591.564
   234.5 1590.78   244.2 1591.66   263.8 1596.17   273.6 1597.98   283.4 1599.66
   293.2 1601.04     303 1601.72   312.8 1601.99   332.4 1602.21
#Mann= 3 ,-1 , 0
       0     .12       0  228.07    .045       0   244.2     .12       0
Bank Sta=228.07,244.2
XS Rating Curve= 0 ,0
Exp/Cntr=0.3,0.1

Type RM Length L Ch R = 1 ,1084.9  ,192,207.7,223.1
XS GIS Cut Line= 4
      1840031.73      221148.758     1840182.822       221160.84
     1840344.384      220866.129     1840462.503      220792.855
#Sta/Elev= 30
       0 1595.95      19 1592.62    37.9 1590.04    56.8 1588.39   73.061587.406
   151.6 1584.66   180.4 1586.18   199.6 1588.59   218.8  1591.5   228.4 1592.28
     238 1592.52   266.8 1590.79   276.4 1590.73   295.6 1591.75   343.6 1595.36
   353.2 1595.09   362.8 1593.95   401.2 1587.06   410.8 1586.25  416.211587.058
   420.4 1587.69   439.6 1595.24   449.2 1596.01   487.7 1595.91   524.7 1594.07
   543.3 1593.56   552.5 1595.01   561.8 1598.04   571.1 1601.92   626.7    1628
#Mann= 3 ,-1 , 0
   73.06     .12       0   401.2    .045       0  416.21     .12       0
#XS Ineff= 2 , 0
          345.53 1596.69
Permanent Ineff=
       F       F
Bank Sta=401.2,416.21
XS Rating Curve= 0 ,0
Exp/Cntr=0.3,0.1

Type RM Length L Ch R = 1 ,877.2   ,236.8,228,218.7
XS GIS Cut Line= 4
     1840040.411      221186.735     1840177.823      221197.696
     1840549.895      221048.221     1840604.647       220952.36
#Sta/Elev= 30
       0 1591.63    18.4 1588.16    36.8 1586.49    73.5 1584.74  112.731584.277
     177 1584.55   186.8 1585.97   206.3 1590.33   216.1  1591.4   225.9 1591.06
   284.6 1585.11   304.1 1584.09     353 1588.88   362.8 1588.26  396.441581.224
   401.9 1580.53   411.7 1581.26   431.2 1585.91     441 1586.57   460.6 1586.38
   519.3 1584.09   538.8  1583.7     548 1584.13   557.2 1586.19   566.4  1590.6
     594 1607.49   603.2  1612.4   612.4 1616.05   621.6 1618.47   649.2 1623.46
#Mann= 3 ,-1 , 0
  112.73     .12       0  396.44    .045       0   411.7     .12       0
#XS Ineff= 2 , 0
          352.41 1593.76
Permanent Ineff=
       F       F
Bank Sta=396.44,411.7
XS Rating Curve= 0 ,0
Exp/Cntr=0.3,0.1

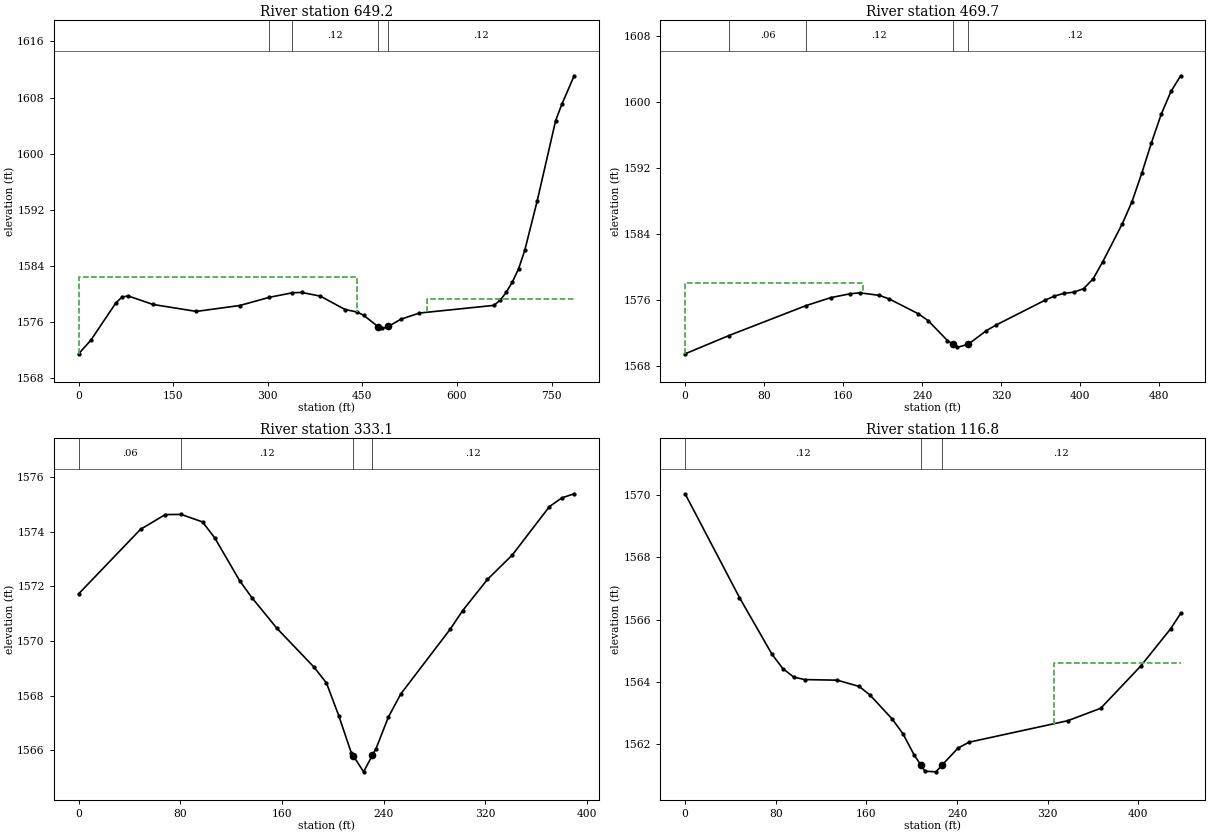
Type RM Length L Ch R = 1 ,649.2   ,192.1,179.6,165.8
XS GIS Cut Line= 4
     1840147.008       221528.25      1840331.47      221500.038
     1840673.051      221160.463     1840719.057      221052.339
#Sta/Elev= 30
       0 1571.51    19.6 1573.48    58.9 1578.74    68.8  1579.6    78.6 1579.75
   117.9 1578.54   186.6 1577.55   255.4 1578.39  302.661579.563  339.021580.206
   353.7 1580.25   383.2 1579.73   422.5 1577.82   442.2 1577.45     452 1576.99
  474.94 1575.38   481.5 1575.12   491.3 1575.42     511 1576.44   540.5 1577.32
   658.4 1578.41   668.3 1579.13     678 1580.26   687.8 1581.74   697.6  1583.6
   707.4 1586.23     727 1593.23   756.4 1604.71   766.2 1607.04   785.8  1611.1
#Mann= 4 ,-1 , 0
  302.66     .06       0  339.02     .12       0  474.94    .045       0
   491.3     .12       0
#XS Ineff= 2 , 0
          442.08 1582.42     553         1579.32
Permanent Ineff=
       F       F
Bank Sta=474.94,491.3
XS Rating Curve= 0 ,0
Exp/Cntr=0.3,0.1

Type RM Length L Ch R = 1 ,469.7   ,126.1,136.6,146.8
XS GIS Cut Line= 2
     1840656.991      221596.609     1840762.242      221106.158
#Sta/Elev= 30
       0 1569.44   44.441571.663  122.211575.283   147.5 1576.26   167.2 1576.73
     177 1576.84   196.7 1576.53   206.6  1576.1   236.1  1574.3   245.9 1573.48
   265.6 1571.05  270.91 1570.59   275.4 1570.22   286.7 1570.61   304.9 1572.25
   314.7 1572.93   363.9 1575.92   373.8 1576.45   383.6 1576.78   393.4 1576.92
   403.3 1577.34   413.1 1578.55   422.9 1580.64   442.6 1585.23   452.4 1587.91
   462.3 1591.36   472.1 1595.07     482 1598.52   491.8 1601.27   501.6 1603.17
#Mann= 4 ,-1 , 0
   44.44     .06       0  122.21     .12       0  270.91    .045       0
   286.7     .12       0
#XS Ineff= 2 , 0
          180.53 1578.01
Permanent Ineff=
       F       F
Bank Sta=270.91,286.7
XS Rating Curve= 0 ,0
Exp/Cntr=0.3,0.1

Type RM Length L Ch R = 1 ,333.1   ,212.9,216.2,219.3
XS GIS Cut Line= 2
     1840696.053      221565.142     1840938.383      221259.651
#Sta/Elev= 26
       0 1571.72    48.7 1574.08    68.2 1574.62    80.71574.625    97.5 1574.35
   107.2 1573.76   126.7  1572.2   136.5 1571.57     156 1570.46   185.2 1569.04
     195 1568.46   204.7 1567.26   214.5 1565.91   216.2 1565.79   224.2 1565.21
   231.2 1565.82     234 1566.06   243.7 1567.21   253.5 1568.06   292.4 1570.43
   302.2 1571.11   321.7 1572.25   341.2 1573.14   370.4 1574.91   380.2 1575.23
   389.9 1575.38
#Mann= 4 ,-1 , 0
       0     .06       0    80.7     .12       0   216.2    .045       0
   231.2     .12       0
Bank Sta=216.2,231.2
XS Rating Curve= 0 ,0
Exp/Cntr=0.3,0.1

Type RM Length L Ch R = 1 ,116.8   ,114.7,116.8,118.9
XS GIS Cut Line= 4
      1840795.88      221569.483     1840938.601      221587.776
     1841100.059      221434.131     1841100.524      221363.602
#Sta/Elev= 23
       0 1570.04      48 1566.71    76.7 1564.89    86.3 1564.43    95.9 1564.16
   105.5 1564.08   134.3 1564.06   153.6 1563.86   163.3 1563.58   182.6 1562.82
   192.3 1562.34     202 1561.67   208.2 1561.33   211.7 1561.14   221.4 1561.12
  226.59 1561.33   240.8 1561.88   250.5 1562.07   337.7 1562.76   366.8 1563.16
     402 1564.51   428.5 1565.71   437.3  1566.2
#Mann= 3 ,-1 , 0
       0     .12       0   208.2    .045       0  226.59     .12       0
#XS Ineff= 2 , 0
                          325.59          1564.6
Permanent Ineff=
       F       F
Bank Sta=208.2,226.59
XS Rating Curve= 0 ,0
Exp/Cntr=0.3,0.1

Chan Stop Cuts=-1
Use User Specified Reach Order=0
Composite Channel Slope=5